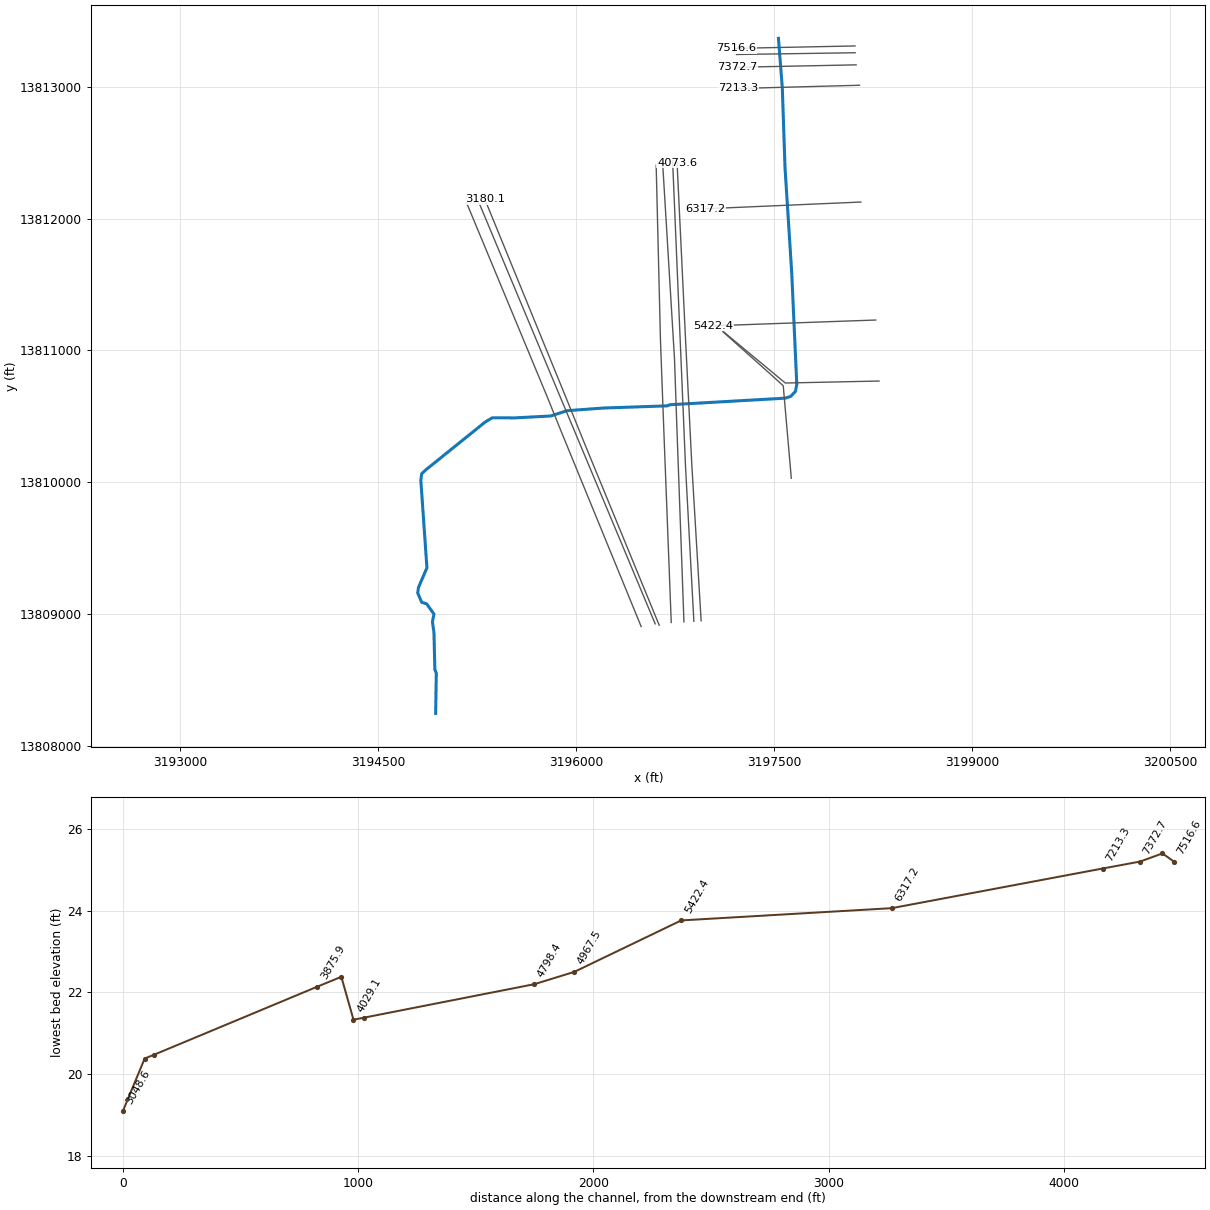
--- B114-00-00.prj (project) ---

Proj Title=B114-00-00
Current Plan=p01
Default Exp/Contr=.3,.1
English Units
Geom File=g08
Flow File=f03
Flow File=f01
Plan File=p04
Plan File=p01
Y Axis Title=Elevation
X Axis Title(PF)=Main Channel Distance
X Axis Title(XS)=Station
BEGIN DESCRIPTION:
Watershed: Armand Bayou
Stream name:
HCFCD Unit B114-00-00
(Flood Hazard, Floodway) Model
10. 2 1 0.2% Event
Filename: B114-00-00.prj
Prepared by: Ty Turner 2-2003, Revised by Sean Sutton 6-10-2003
Reviewed by:
STATUS: Final RAS
END DESCRIPTION:
DSS Export Rating Curves= 0
DSS Export Rating Curve Sorted= 0
DSS Export Volume Flow Curves= 0
DXF OffsetX= 0
DXF OffsetY= 0
DXF ScaleX= 1
DXF ScaleY= 10

--- B114-00-00.p01 (plan) ---

Plan Title=Floodway
Version=Version 3.0.1  Mar 2001
Short Identifier=Floodway0607
Geom File=g08
Flow File=f01
Subcritical Flow
K Sum by GR= 0
Std Step Tol= 0.01
Critical Tol= 0.01
Num of Std Step Trials= 20
Max Error Tol= 0.3
Flow Tol Ratio= 0.001
Split Flow NTrial= 30
Split Flow Tol= 0.02
Split Flow Ratio= 0.02
Log Output Level= 0
Friction Slope Method= 0
Unsteady Friction Slope Method= 2
Secant Critical Depth
Global Vel Dist= 0 , 0 , 0
Global Log Level= 0
CheckData=True
Encroach Param=-1 ,0,0, 2
Encroach River=B114-00-00
Encroach Reach=3
Encroach Node=7516.6
       1  554.27  596.26
Encroach Node=7468.0
       1  545.82  593.55
Encroach Node=7420
       4       1
Encroach Node=7372.7
       1  554.27  597.74
Encroach Node=7213.3
       1  564.49  615.99
Encroach Node=6317.2
       1  534.62  576.05
Encroach Node=5422.4
       1  595.64  671.41
Encroach Node=4967.5
       1     596  667.41
Encroach Node=4798.4
       1  573.18  649.24
Encroach Node=4073.6
       1 1618.36 1690.55
Encroach Node=4029.1
       1 1621.54 1682.58
Encroach Node=4003
       1 3.4E+38 3.4E+38
Encroach Node=3977.4
       1 1626.69 1687.73
Encroach Node=3875.9
       1 1613.84 1688.92
Encroach Node=3180.1
       1 1735.76    1792
Encroach Node=3141.4
       1    1727 1775.77
Encroach Node=3095
       1 3.4E+38 3.4E+38
Encroach Node=3048.6
       1  1711.8  1757.9
Encroach Node=2897.2
       1 1799.67 1852.26
Encroach Node=2608.1
       1 1745.64 1791.34
Encroach Node=2521.5
       1 1724.89 1775.13
Encroach Node=1936.139
       1  757.31  807.35
Encroach Node=1815.820
       1  739.62  791.21
Encroach Node=1231.2
       1  950.35 1018.21
Encroach Node=1163.034
       1 1115.54 1183.84
Encroach Node=1104
       1 3.4E+38 3.4E+38
Encroach Node=1045.9
       1  428.25  496.93
Encroach Node=819.5
       1   82.25     128
Encroach Node=697.7
       1  609.25  671.93
Encroach Node=113.2
       1  711.31   771.4
Encroach Reach=B114-00-00_0001
Encroach Node=7516.6
       1  554.27  596.26
Encroach Node=7468.0
       1  545.82  593.55
Encroach Node=7420
       4       1
Encroach Node=7372.7
       1  554.27  597.74
Encroach Node=7213.3
       1  564.49  615.99
Encroach Node=6317.2
       1  534.62  576.05
Encroach Node=5422.4
       1  595.64  671.41
Encroach Node=4967.5
       1     596  667.41
Encroach Node=4798.4
       1  573.18  649.24
Encroach Node=4073.6
       1 1618.36 1690.55
Encroach Node=4029.1
       1 1621.54 1682.58
Encroach Node=4003
       1 3.4E+38 3.4E+38
Encroach Node=3977.4
       1 1626.69 1687.73
Encroach Node=3875.9
       1 1613.84 1688.92
Encroach Node=3180.1
       1 1735.76    1792
Encroach Node=3141.4
       1    1727 1775.77
Encroach Node=3095
       1 3.4E+38 3.4E+38
Encroach Node=3048.6
       1  1711.8  1757.9
Encroach Node=2897.2
       1 1799.67 1852.26
Encroach Node=2608.1
       1 1745.64 1791.34
Encroach Node=2521.5
       1 1724.89 1775.13
Encroach Node=1936.139
       1  757.31  807.35
Encroach Node=1815.820
       1  739.62  791.21
Encroach Node=1231.2
       1  950.35 1018.21
Encroach Node=1163.034
       1 1115.54 1183.84
Encroach Node=1104
       1 3.4E+38 3.4E+38
Encroach Node=1045.9
       1  428.25  496.93
Encroach Node=819.5
       1   82.25     128
Encroach Node=697.7
       1  609.25  671.93
Encroach Node=113.2
       1  711.31   771.4
Computation Interval=1HOUR
Output Interval=1HOUR
Run HTab= 0
Run UNet= 0
Run PostProcess= 0
UNET Theta= 1
UNET ZTol= 0.02
UNET ZSATol= 0.1
UNET MxIter= 20
UNET MaxInSteps= 20
UNET DtIC= 0
UNET DtMin= 0
UNET MaxCRTS= 20
UNET WFStab= 2
UNET SFStab= 1
UNET WFX= 1
UNET SFX= 1
UNET Convert EG Bridges=-1
UNET Use Existing IB Tables=-1
Instantaneous Interval=1HOUR
Write IC File= 0
IC Time=0
Write Velocity= 0
Write Detailed= 0

--- B114-00-00.p04 (plan) ---

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Plan Title=FEMA Effective June 2007
Short Identifier=FEMAeff0607
Geom File=g08
Flow File=f03
Encroach Param=-1 ,0,0, 0
DSS File=dss

--- B114-00-00.f01 (steady flow) ---

Flow Title=Floodway
Version=Version 3.0.1  Mar 2001
Number of Profiles= 2
Profile Names=1PCT_100yr, 1PCTFloodway_100yrFW
River Rch & RM=B114-00-00,B114-00-00_0001               ,7516.6
     159     159
River Rch & RM=B114-00-00,B114-00-00_0001               ,7468.0
     177     177
River Rch & RM=B114-00-00,B114-00-00_0001               ,7213.3
     196     196
River Rch & RM=B114-00-00,B114-00-00_0001               ,6317.2
     305     305
River Rch & RM=B114-00-00,B114-00-00_0001               ,5422.4
     413     413
River Rch & RM=B114-00-00,B114-00-00_0001               ,4967.5
     468     468
River Rch & RM=B114-00-00,B114-00-00_0001               ,4073.6
     576     576
River Rch & RM=B114-00-00,B114-00-00_0001               ,3180.1
     685     685
River Rch & RM=B114-00-00,B114-00-00_0001               ,2897.2
     719     719
River Rch & RM=B114-00-00,B114-00-00_0001               ,2521.5
     764     764
River Rch & RM=B114-00-00,B114-00-00_0001               ,1936.139
     835     835
River Rch & RM=B114-00-00,B114-00-00_0001               ,1231.2
     921     921
River Rch & RM=B114-00-00,B114-00-00_0001               ,819.5
     970     970
River Rch & RM=B114-00-00,B114-00-00_0001               ,113.2
    1056    1056
Boundary for River Rch & Prof#=B114-00-00,B114-00-00_0001               , 1
Up Type= 0
Dn Type= 3
Dn Slope=.0011
Boundary for River Rch & Prof#=B114-00-00,B114-00-00_0001               , 2
Up Type= 0
Dn Type= 3
Dn Slope=.0011
DSS Import GetInterval= 0
DSS Import GetPeak= 0
DSS Import FillOption= 0

--- B114-00-00.f03 (steady flow) ---

Flow Title=FEMA Effective June 2007
Version=Version 3.0.1  Mar 2001
Number of Profiles= 4
Profile Names=10PCT_10yr, 2PCT_50yr, 1PCT_100yr, 0.2PCT_500yr
River Rch & RM=B114-00-00,B114-00-00_0001               ,7516.6
      94     137     159     223
River Rch & RM=B114-00-00,B114-00-00_0001               ,7468.0
     105     152     177     248
River Rch & RM=B114-00-00,B114-00-00_0001               ,7213.3
     116     169     196     275
River Rch & RM=B114-00-00,B114-00-00_0001               ,6317.2
     181     262     305     427
River Rch & RM=B114-00-00,B114-00-00_0001               ,5422.4
     245     355     413     579
River Rch & RM=B114-00-00,B114-00-00_0001               ,4967.5
     277     402     468     656
River Rch & RM=B114-00-00,B114-00-00_0001               ,4073.6
     342     496     576     808
River Rch & RM=B114-00-00,B114-00-00_0001               ,3180.1
     406     589     685     959
River Rch & RM=B114-00-00,B114-00-00_0001               ,2897.2
     426     618     719    1008
River Rch & RM=B114-00-00,B114-00-00_0001               ,2521.5
     453     657     764    1071
River Rch & RM=B114-00-00,B114-00-00_0001               ,1936.139
     495     718     835    1171
River Rch & RM=B114-00-00,B114-00-00_0001               ,1231.2
     546     792     921    1290
River Rch & RM=B114-00-00,B114-00-00_0001               ,819.5
     575     834     970    1360
River Rch & RM=B114-00-00,B114-00-00_0001               ,113.2
     626     908    1056    1480
Boundary for River Rch & Prof#=B114-00-00,B114-00-00_0001               , 1
Up Type= 0
Dn Type= 3
Dn Slope=.0011
Boundary for River Rch & Prof#=B114-00-00,B114-00-00_0001               , 2
Up Type= 0
Dn Type= 3
Dn Slope=.0011
Boundary for River Rch & Prof#=B114-00-00,B114-00-00_0001               , 3
Up Type= 0
Dn Type= 3
Dn Slope=.0011
Boundary for River Rch & Prof#=B114-00-00,B114-00-00_0001               , 4
Up Type= 0
Dn Type= 3
Dn Slope=.0011
DSS Import GetInterval= 0
DSS Import GetPeak= 0
DSS Import FillOption= 0

--- B114-00-00.g08 (geometry) ---

Geom Title=B114-00-00 June 2007
Version=Version 3.0.1  Mar 2001

River Reach=B114-00-00      ,B114-00-00_0001
Reach XY= 30
     3197531.689    13813367.661      3197561.06    13812991.113
     3197581.536    13812385.969     3197632.557    13811584.381
      3197670.49    13810741.797     3197660.716    13810688.389
     3197624.715     13810650.47     3197582.801    13810636.896
     3196710.996    13810587.064     3196687.857    13810578.539
     3196203.108     13810561.84     3195929.446      13810541.6
     3195808.564    13810501.814     3195536.453    13810487.205
     3195364.597    13810487.964     3195311.212    13810455.846
     3194865.031    13810095.603     3194830.477     13810063.19
     3194823.868    13810014.718     3194870.157    13809349.514
     3194806.003    13809200.204     3194800.179    13809158.518
     3194830.625    13809087.882       3194868.6    13809075.568
     3194923.476    13808997.721     3194911.906    13808940.655
     3194923.476     13808857.34     3194930.097    13808577.477
      3194941.06    13808550.912     3194936.237    13808244.772

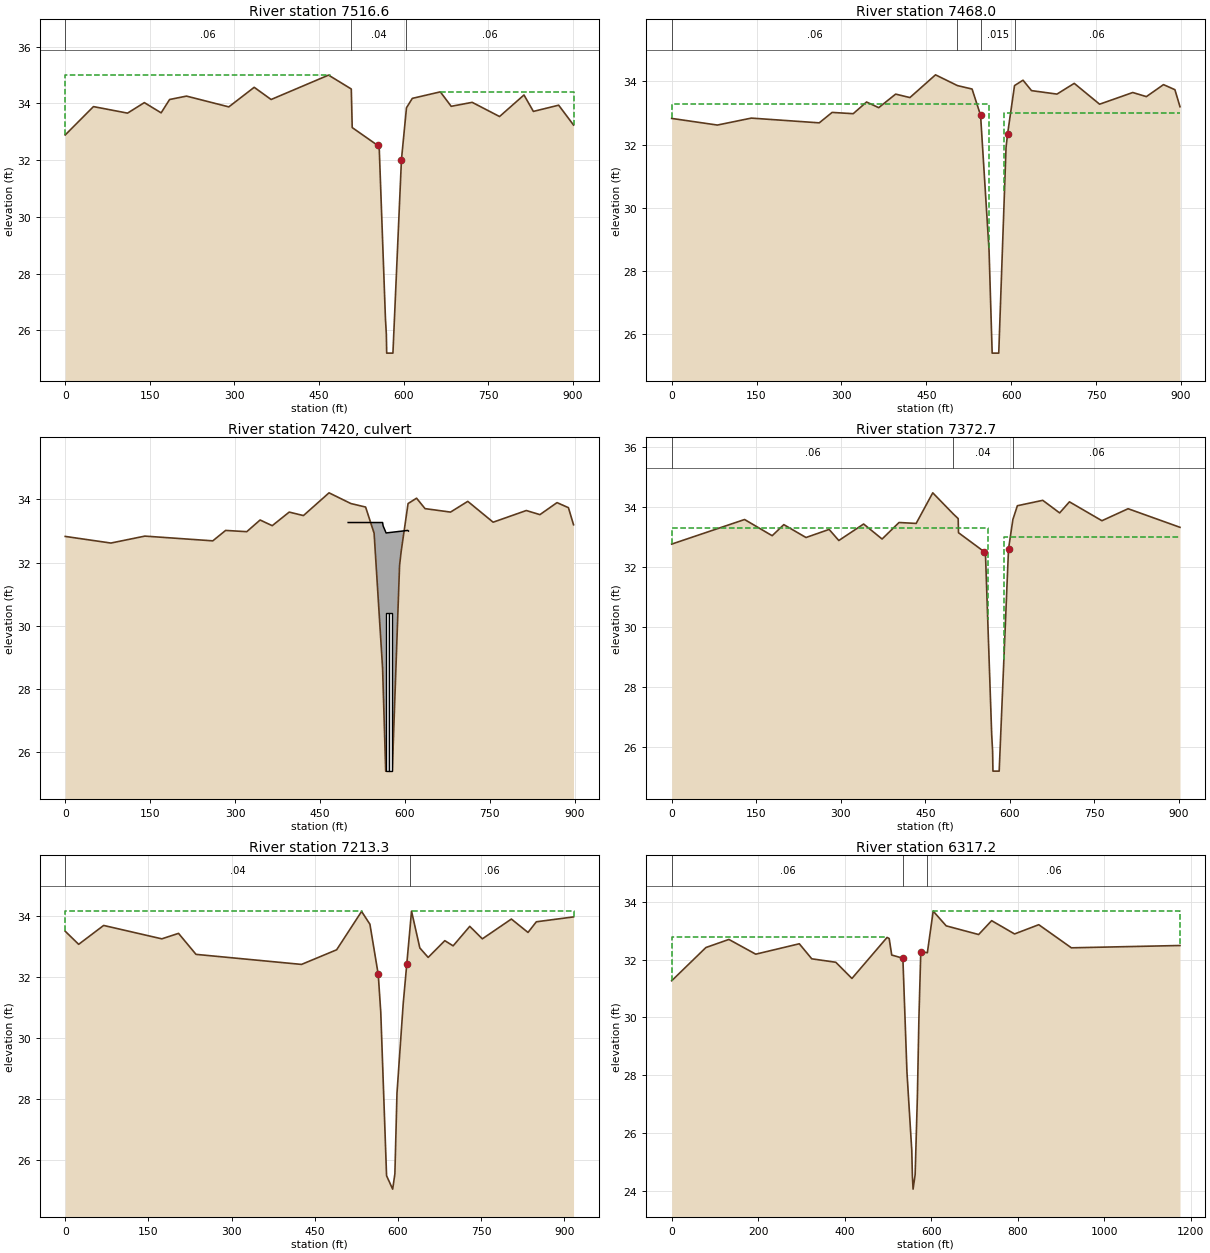
Type RM Length L Ch R = 1 ,7516.6  ,48.77,48.58,48.36
BEGIN DESCRIPTION:
XS4 (Lidar) (Survey copied from 7372 - from 508.96-581.15)
Due to the length of cross-section and detail of the ground data, ineffective flow areas have been utilized to account for pockets or storage areas, disconnected portions of the cross-section, and/or inactive flow areas that do not actively convey flow downstream.
END DESCRIPTION:
XS GIS Cut Line= 4
      3198111.72    13813309.889     3197611.822     13813299.79
     3197486.107     13813297.25     3197210.481    13813291.682
#Sta/Elev= 30
       0   32.89   50.09   33.89  110.53   33.66  140.37   34.03  170.11   33.67
  185.11   34.14  215.12   34.26  290.13   33.88  335.14   34.57  365.15   34.14
  467.01      35  507.32   34.51  508.96   33.15  554.27   32.52  556.77   32.48
  567.87   26.42   569.5   25.86  570.08    25.2  581.15    25.2  596.26   32.02
   605.2   33.85  615.54   34.18  665.21   34.41  684.49    33.9   721.7   34.04
  770.23   33.54  813.57    34.3  830.24   33.72  875.04   33.94  901.42   33.24
#Mann= 3 ,-1 , 0
       0     .06       0  507.32     .04       0   605.2     .06       0
#XS Ineff= 2 , 0
          469.38   35.01  665.05           34.42
Permanent Ineff=
       F       F
Bank Sta=554.27,596.26
XS Rating Curve= 0
Exp/Cntr=.5,.3

Type RM Length L Ch R = 1 ,7468.0  ,95.03,95.27,95.41
BEGIN DESCRIPTION:
B114-00-00-s1 XS1
Due to the length of cross-section and detail of the ground data, ineffective flow areas have been utilized to account for pockets or storage areas, disconnected portions of the cross-section, and/or inactive flow areas that do not actively convey flow downstream.
END DESCRIPTION:
XS GIS Cut Line= 4
     3198112.401    13813258.326     3197612.457    13813250.901
     3197484.202    13813248.996     3197214.296    13813244.988
#Sta/Elev= 30
       0   32.83   80.76   32.62  140.77   32.84  260.78   32.69  283.46   33.02
  320.79   32.98  344.37   33.35   365.8   33.17   395.8    33.6  420.95   33.49
  466.19   34.21  504.85   33.87  530.81   33.76  545.82   32.93  560.82   28.65
   566.3    25.4  577.93    25.4  590.82   31.91  593.55   32.34  605.82   33.87
  620.82   34.04  635.83   33.71  680.83    33.6  711.32   33.94  756.15   33.28
  814.73   33.65  838.81   33.52  869.03    33.9  889.19   33.74   898.2    33.2
#Mann= 4 ,-1 , 0
       0     .06       0  504.85     .04       0  545.82    .015       0
  605.82     .06       0
#XS Ineff= 2 , 0
       0   560.5    33.3  588.07       0      33
Permanent Ineff=
       F       F
Bank Sta=545.82,593.55
XS Rating Curve= 0
Exp/Cntr=.5,.3

Type RM Length L Ch R = 2 ,7420    ,,,
BEGIN DESCRIPTION:
Structure s1 - Wisdom Rd
END DESCRIPTION:
Bridge Culvert--1,0,-1,-1, 0
Deck Dist Width WeirC Skew NumUp NumDn MinLoCord MaxHiCord MaxSubmerge Is_Ogee
14.636,64.7,2.6,0, 7, 7, , , .95, 0, 0,0,,
     500     545  560.78  561.81     567  605.28  606.53
   33.27   33.27   33.27   33.16   32.94   33.02      33
                                                        
     500     545  560.78  561.81     567  605.28  606.53
   33.27   33.27   33.27   33.16   32.94   33.02      33
                                                        
BR Coef=-1 , 0 , 0 ,, 0 ,,,.8,-1,1.2,1,
WSPro=,,,, 1 ,,,, 0 ,,,, 0 ,,,,-1 ,-1 ,-1 , 0 , 0 , 0 , 0 , 0
Multiple Barrel Culv=2,5,5,64.7,.013,.4,1,8,1,25.4,25.2, 2,Culvert #1  , 0 ,14.636
   568.8  572.58  575.43  578.65
Culvert Bottom n=.013
BC Design=,, 0 ,, 0 ,,,,,,
BC HTab HWMax=34.22

Type RM Length L Ch R = 1 ,7372.7  ,159.09,159.45,159.55
BEGIN DESCRIPTION:
B114-00-00-sv1 (Survey 508.96 to 605.46) XS2
Due to the length of cross-section and detail of the ground data, ineffective flow areas have been utilized to account for pockets or storage areas, disconnected portions of the cross-section, and/or inactive flow areas that do not actively convey flow downstream.
END DESCRIPTION:
XS GIS Cut Line= 4
     3198119.973    13813166.448     3197620.076    13813156.298
     3197494.996    13813153.758     3197218.147    13813148.137
#Sta/Elev= 30
       0   32.77  129.37   33.59  178.36   33.05  198.99   33.42  238.38   32.99
   279.4   33.26  296.57   32.89  340.65   33.44   373.4   32.94  403.41   33.49
  433.84   33.46   463.3   34.48     500   33.77  508.43   33.62  508.96   33.15
  554.27   32.52  556.77   32.48  567.87   26.42   569.5   25.86  570.08    25.2
  581.15    25.2  597.74   32.61  605.46   33.59  613.45   34.05  658.46   34.23
  688.47   33.81  705.81   34.18  763.49   33.55  809.93   33.95  902.01   33.33
#Mann= 3 ,-1 , 0
       0     .06       0     500     .04       0  605.46     .06       0
#XS Ineff= 2 , 0
       0  560.86    33.3  589.45       0      33
Permanent Ineff=
       F       F
Bank Sta=554.27,597.74
XS Rating Curve= 0
Exp/Cntr=.5,.3

Type RM Length L Ch R = 1 ,7213.3  ,895.04,896.07,896.27
BEGIN DESCRIPTION:
XS1 (Interpolated Flow Line)
Due to the length of cross-section and detail of the ground data, ineffective flow areas have been utilized to account for pockets or storage areas, disconnected portions of the cross-section, and/or inactive flow areas that do not actively convey flow downstream.
END DESCRIPTION:
XS GIS Cut Line= 4
     3198145.928     13813011.59     3197646.107    13812998.202
     3197503.885    13812994.393     3197229.604    13812987.046
#Sta/Elev= 30
       0    33.5   24.29   33.07   69.31   33.69  174.21   33.25  204.36   33.43
  235.88   32.74  426.13   32.41  489.46   32.89  534.47   34.15  549.48   33.73
  564.49   32.08  569.05   30.84  579.49   25.47   590.5   25.03   594.5   25.53
  598.28   28.18   609.5   31.12  615.99   32.43  621.34   33.51  624.51   34.16
  639.51   32.95  654.52   32.64  684.53   33.19  699.53   33.02  729.54   33.66
  752.22   33.25  804.57    33.9  834.58   33.46  849.59   33.81  916.65   33.97
#Mann= 2 ,-1 , 0
       0     .04       0  621.34     .06       0
#XS Ineff= 2 , 0
          534.87   34.15  624.56           34.17
Permanent Ineff=
       F       F
Bank Sta=564.49,615.99
XS Rating Curve= 0
Exp/Cntr=.3,.1

Type RM Length L Ch R = 1 ,6317.2  ,894.89,894.81,894.44
BEGIN DESCRIPTION:
B114-00-00-v1 (Survey 508.83 to 591.22)
Due to the length of cross-section and detail of the ground data, ineffective flow areas have been utilized to account for pockets or storage areas, disconnected portions of the cross-section, and/or inactive flow areas that do not actively convey flow downstream.
END DESCRIPTION:
XS GIS Cut Line= 4
     3198155.794    13812125.316     3197656.266    13812103.598
     3197481.028    13812095.979       3196981.5     13812074.26
#Sta/Elev= 30
       0   31.27   79.13   32.42  132.33    32.7  194.42   32.19  295.14   32.55
  323.91   32.03  379.51   31.91  416.83   31.35  498.07   32.77  502.94   32.73
  508.83   32.16  534.62   32.05  534.81   31.97  544.04   28.11  555.18    25.4
  556.64    24.5  558.21   24.06  562.97   24.56  568.19   27.28   571.7   29.97
  576.05   32.28  591.22   32.24  604.72   33.68  634.75   33.17  709.82   32.87
  739.85   33.35  792.85   32.89  848.84   33.21  924.21   32.41  1175.4   32.49
#Mann= 3 ,-1 , 0
       0     .06       0  534.81     .04       0  591.22     .06       0
#XS Ineff= 2 , 0
          497.95   32.78  604.34           33.69
Permanent Ineff=
       F       F
Bank Sta=534.62,576.05
XS Rating Curve= 0
Exp/Cntr=.3,.1

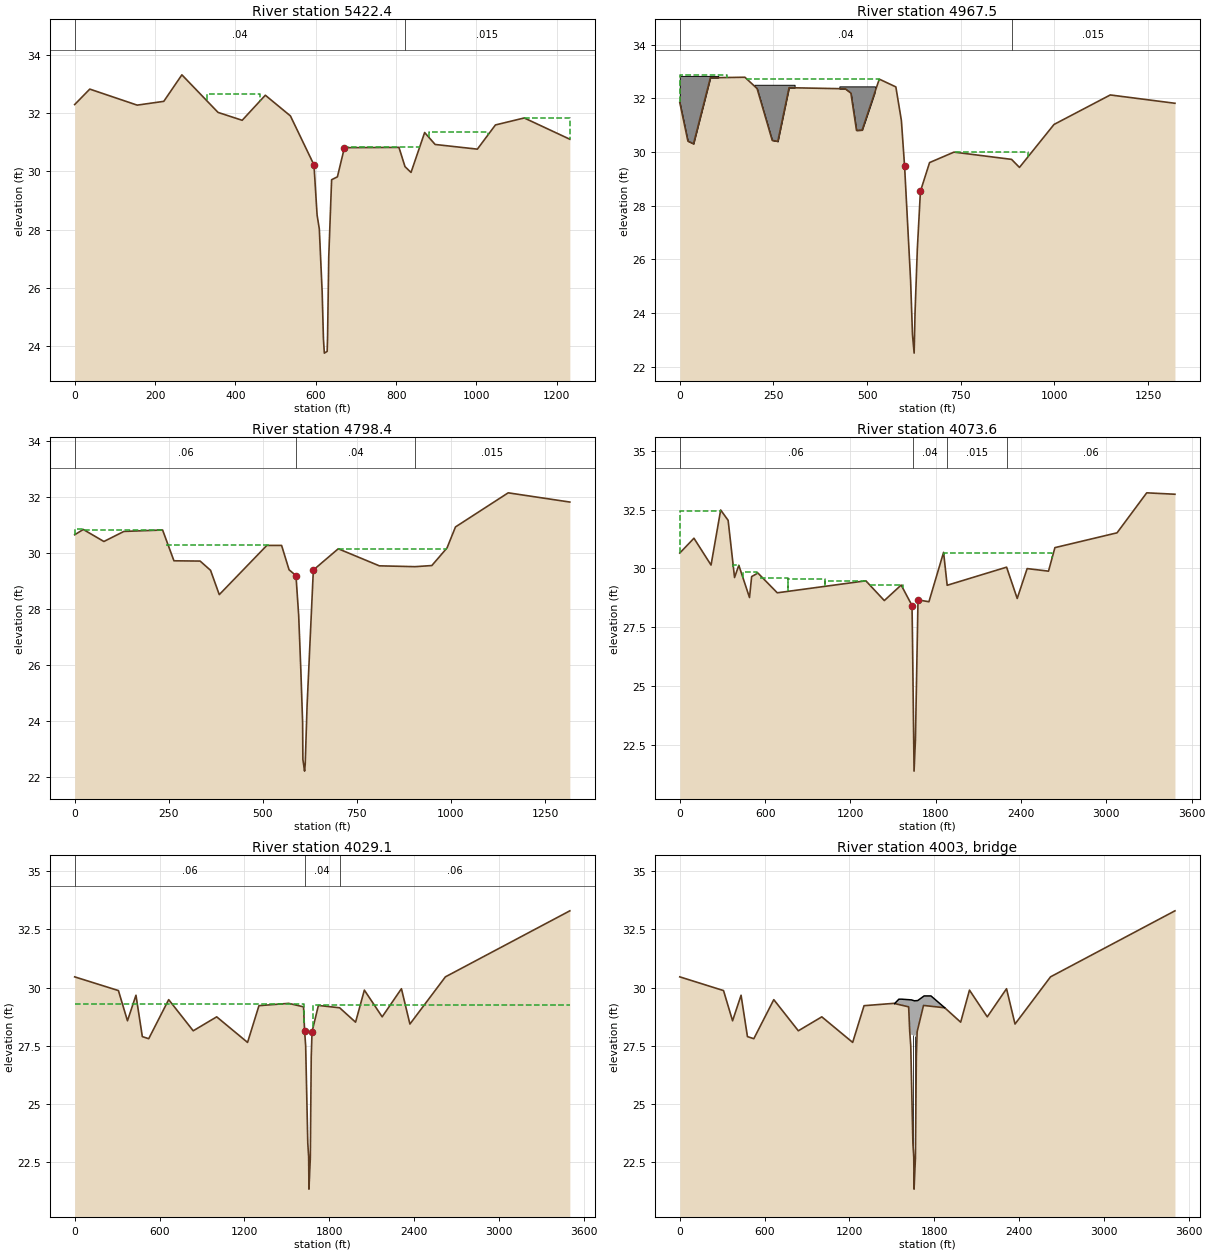
Type RM Length L Ch R = 1 ,5422.4  ,455.47,454.89,454.23
BEGIN DESCRIPTION:
B114-00-00-v2 (Survey 560.98 to 653.99)
Due to the length of cross-section and detail of the ground data, ineffective flow areas have been utilized to account for pockets or storage areas, disconnected portions of the cross-section, and/or inactive flow areas that do not actively convey flow downstream.
END DESCRIPTION:
XS GIS Cut Line= 4
     3198268.332    13811229.916     3197768.647    13811212.168
     3197536.266    13811203.914     3197036.581    13811186.166
#Sta/Elev= 30
       0   32.29   37.61   32.82  155.59   32.27  221.83    32.4  266.86   33.31
  356.91   32.02  416.95   31.75  474.56   32.61  537.03    31.9  595.64   30.22
   603.4    28.5  608.94   28.02  616.03   25.86  619.21   24.25  621.46   23.76
  628.48   23.82  629.54   24.35   632.4   27.05  639.56   29.71  653.99   29.81
  671.41   30.81   807.2   30.82  822.21   30.16  837.21   29.96  871.13   31.33
  897.25   30.92 1002.32   30.76 1047.35   31.59 1119.07   31.83 1232.53    31.1
#Mann= 2 ,-1 , 0
       0     .04       0  822.21    .015       0
#XS Ineff= 4 ,-1
  328.19  461.98   32.65  670.93  860.65   30.83  881.89 1027.72   31.34
 1119.08 1234.52   31.83
Permanent Ineff=
       F       F       F       F
Bank Sta=595.64,671.41
XS Rating Curve= 0
Exp/Cntr=.3,.1

Type RM Length L Ch R = 1 ,4967.5  ,232.03,169.1,125.42
BEGIN DESCRIPTION:
B114-00-00-v3 (Survey 591.57 to 660.99). Non-conveyance, storage areas assumed full; therefore blocked obstructions were used.
Due to the length of cross-section and detail of the ground data, ineffective flow areas have been utilized to account for pockets or storage areas, disconnected portions of the cross-section, and/or inactive flow areas that do not actively convey flow downstream.
END DESCRIPTION:
XS GIS Cut Line= 5
     3198293.297    13810766.898     3197793.409    13810756.294
     3197583.885     13810751.85     3197497.536    13810823.596
     3197112.962    13811143.132
#Sta/Elev= 30
       0   31.84   21.66    30.4   36.66    30.3   81.67   32.76  173.84   32.78
  206.33   32.36  246.71   30.43  261.71   30.39  291.72   32.39  441.75   32.35
  456.75   32.19  471.76    30.8  486.76   30.81  532.56   32.71  576.78   32.42
  591.57   31.17  600.13   29.46  616.17   25.21  621.22   23.18  625.62    22.5
  628.04   24.01  634.14   26.38  642.41   28.53   666.8    29.6  731.99   29.99
  885.63   29.72  906.79   29.42  998.96   31.02 1149.21   32.12 1321.84   31.81
#Mann= 2 ,-1 , 0
       0     .04       0  885.63    .015       0
#XS Ineff= 3 ,-1
    -.01  127.18   32.87  180.63  531.18   32.72  735.37  929.24      30
Permanent Ineff=
       F       F       F
#Block Obstruct= 3 ,-1
    -.01  102.66   32.83   199.2  306.47    32.5     426  521.01   32.44
Bank Sta=600.13,642.41
XS Rating Curve= 0
Exp/Cntr=.3,.1

Type RM Length L Ch R = 1 ,4798.4  ,726.2,724.8,723.5
BEGIN DESCRIPTION:
B114-00-00-v4 (Survey 569.68 to 650.2)
Due to the length of cross-section and detail of the ground data, ineffective flow areas have been utilized to account for pockets or storage areas, disconnected portions of the cross-section, and/or inactive flow areas that do not actively convey flow downstream.
END DESCRIPTION:
XS GIS Cut Line= 5
     3197629.239    13810028.979      3197585.79    13810527.088
     3197568.012    13810730.897     3197485.472    13810806.453
     3197113.354    13811139.451
#Sta/Elev= 30
       0   30.65   22.89   30.84   77.68   30.41  130.86   30.77  233.69   30.82
  263.81   29.72  333.38   29.71  361.06   29.38  384.26   28.51  510.63   30.27
  549.89   30.27  569.68    29.4  588.07   29.19  588.18   29.17  595.27   27.77
  600.99   25.82  605.72   23.94  606.46   22.62  610.92    22.2  612.63   22.45
  617.58   24.54  634.24   29.39  700.46   30.15  809.57   29.54  904.41   29.51
   949.1   29.55  989.48   30.18 1011.93   30.93 1152.05   32.15 1315.84   31.82
#Mann= 3 ,-1 , 0
       0     .06       0  588.07     .04       0  904.41    .015       0
#XS Ineff= 4 ,-1
     -.1   22.82   30.84   25.68  231.25   30.83  243.84  520.14    30.3
  700.68  988.66   30.15
Permanent Ineff=
       F       F       F       F
Bank Sta=588.18,634.24
XS Rating Curve= 0
Exp/Cntr=.3,.1

Type RM Length L Ch R = 1 ,4073.6  ,44.79,44.49,44.19
BEGIN DESCRIPTION:
B114-00-00-sv2 (Survey 1577.45 to 1721.11) XS4
Due to the length of cross-section and detail of the ground data, ineffective flow areas have been utilized to account for pockets or storage areas, disconnected portions of the cross-section, and/or inactive flow areas that do not actively convey flow downstream.
END DESCRIPTION:
XS GIS Cut Line= 6
     3196946.411    13808947.266     3196875.904    13810129.617
      3196858.17    13810485.183     3196845.471    13810739.786
     3196827.487    13811100.381     3196764.098    13812425.082
#Sta/Elev= 30
       0   30.65    99.7   31.28  219.91   30.14  287.67   32.48  340.12   32.04
   385.2   29.61  415.26   30.13  490.39   28.76  505.42   29.65   549.6    29.8
  685.74   28.96 1308.71   29.47 1438.54   28.63 1557.08   29.29 1633.36   28.42
 1636.84   26.98 1647.77   21.38 1657.35    22.7 1675.55   28.66 1752.33   28.58
 1855.37   30.68 1880.63   29.28 2298.54   30.05 2373.24   28.72 2443.16   29.99
 2593.33   29.88 2638.38   30.88 3075.42   31.51 3284.12   33.21 3482.64   33.15
#Mann= 4 ,-1 , 0
       0     .06       0 1636.84     .04       0 1880.63    .015       0
 2298.54     .06       0
#XS Ineff= 8 ,-1
   -8.61   288.7   32.45  376.56  414.22   30.16   445.6  539.74   29.83
  563.91   761.6   29.59   761.6 1022.06   29.54 1024.28 1320.16   29.46
 1338.99 1568.07    29.3 1857.76 2618.08   30.67
Permanent Ineff=
       F       F       F       F       F       F       F       F
Bank Sta=1633.36,1675.55
XS Rating Curve= 0
Exp/Cntr=.5,.3

Type RM Length L Ch R = 1 ,4029.1  ,51.98,51.69,51.39
BEGIN DESCRIPTION:
B114-00-00-s2 (Interpolated Flow Line) XS3
Due to the length of cross-section and detail of the ground data, ineffective flow areas have been utilized to account for pockets or storage areas, disconnected portions of the cross-section, and/or inactive flow areas that do not actively convey flow downstream.
END DESCRIPTION:
XS GIS Cut Line= 5
     3196891.344    13808944.026     3196828.394     13810113.46
     3196812.455    13810492.802     3196802.932    13810719.469
     3196730.193    13812441.568
#Sta/Elev= 30
       0   30.46  309.35   29.87   373.3   28.57  433.39   29.67  478.45   27.89
  523.52    27.8  664.75   29.48  838.26   28.14 1004.21   28.74  1222.5   27.64
 1303.05   29.22 1513.23   29.32 1618.33   29.17 1625.73   28.14 1633.34   27.49
 1648.35   23.31 1654.49   22.71 1656.59   21.33 1666.17   22.66 1672.75   27.03
 1678.38    28.1 1723.42   29.23 1873.55   29.13 1986.18   28.51 2048.42   29.89
 2174.24   28.74 2310.46   29.95 2370.52   28.43 2621.42   30.46 3501.31    33.3
#Mann= 3 ,-1 , 0
       0     .06       0 1625.73     .04       0 1873.55     .06       0
#XS Ineff= 2 , 0
       0 1623.44   29.28 1686.15       0   29.23
Permanent Ineff=
       F       F
Bank Sta=1625.73,1678.38
XS Rating Curve= 0
Exp/Cntr=.5,.3

Type RM Length L Ch R = 3 ,4003    ,,,
BEGIN DESCRIPTION:
Structure s2 - Glenwood
END DESCRIPTION:
Bridge Culvert--1,0,-1,-1, 0
Deck Dist Width WeirC Skew NumUp NumDn MinLoCord MaxHiCord MaxSubmerge Is_Ogee
11.845,24,2.6,0, 9, 6, 29.4259, , .95, 0, 0,0,,
 1519.08 1549.28 1568.44  1637.9 1658.77 1682.32 1727.83 1776.15 1873.55
   29.31    29.5    29.5   29.47   29.43   29.44   29.64   29.64   29.13
      28      28      28   27.97   27.93   27.94      25      25      25
  1546.6 1565.76 1635.22 1656.09 1679.64 1725.15
    29.5    29.5   29.47   29.43   29.44   29.64
      28      28   27.97   27.93   27.94      25
Pier Skew, UpSta & Num, DnSta & Num=  ,1649.63, 2 ,1649.63, 2 , 0 , 0 , 0 ,,
     1.5     1.5
      23 28.2635
     1.5     1.5
      23 28.2635
Pier Skew, UpSta & Num, DnSta & Num=  ,1664.28, 2 ,1664.28, 2 , 0 , 0 , 0 ,,
     1.5     1.5
      23   28.26
     1.5     1.5
      23   28.26
BR Coef=-1 , 1 , 1 ,1.25, 0 ,,,.8,-1,2,0,
WSPro=,,,, 1 ,,,, 0 ,,,, 0 ,,,,-1 ,-1 ,-1 , 0 , 0 , 0 , 0 , 0
BC Design=,, 0 ,, 0 ,,,,,,
BC HTab HWMax=33.3

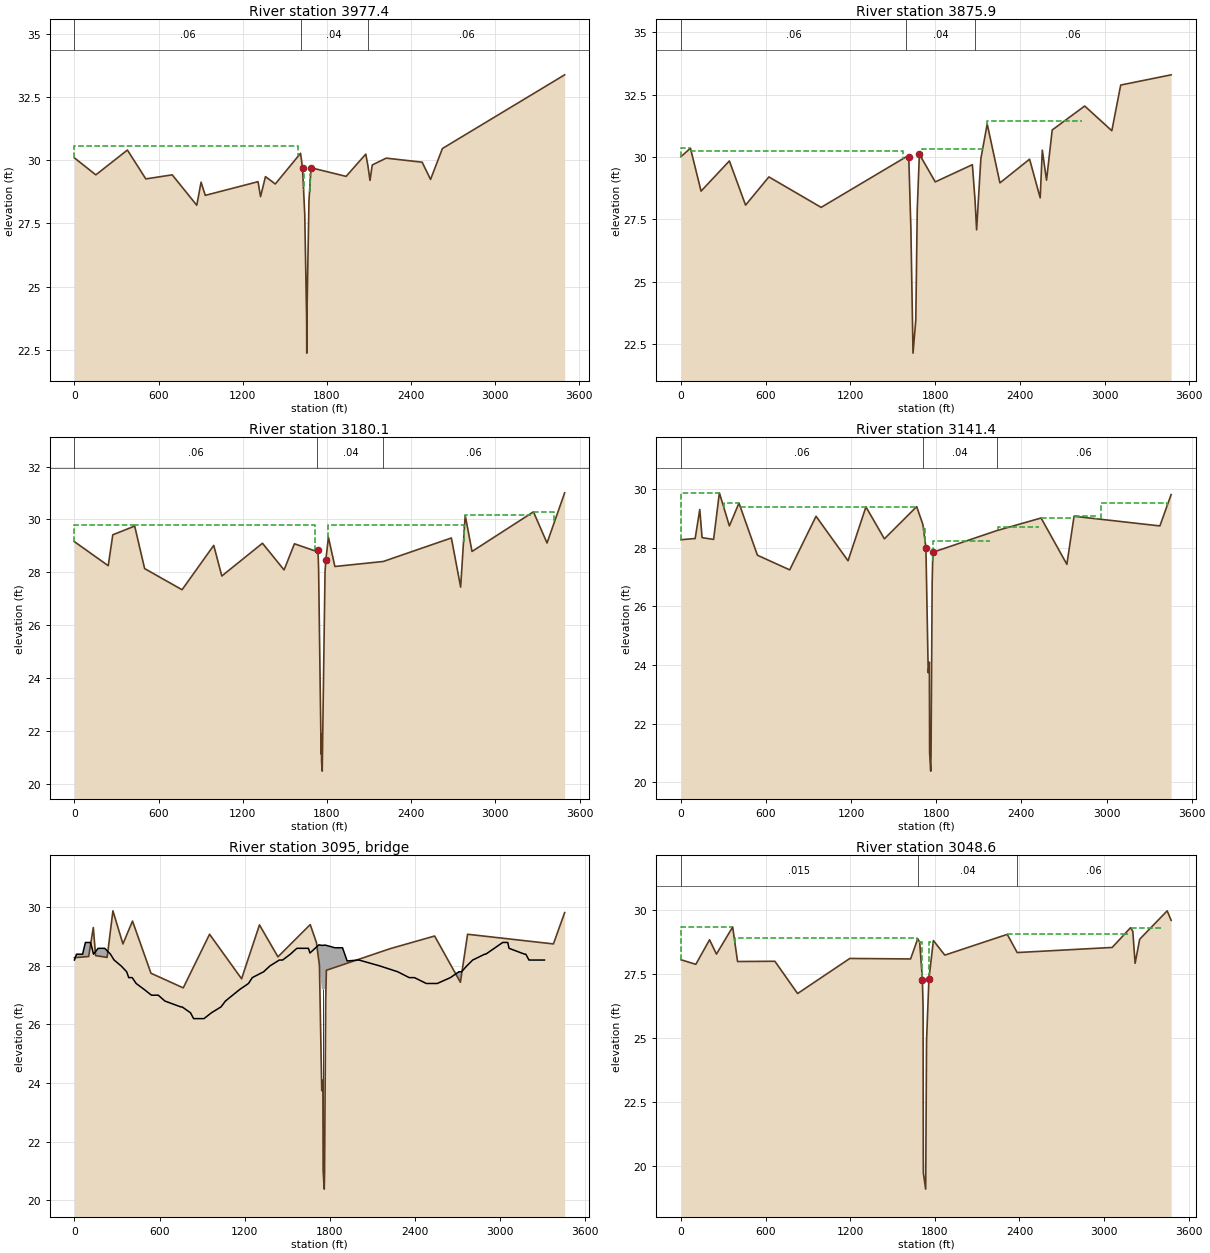
Type RM Length L Ch R = 1 ,3977.4  ,100,101.56,100.2
BEGIN DESCRIPTION:
XS2 (Elev pts adj based on surveyed ds invert and 4029.1)
Due to the length of cross-section and detail of the ground data, ineffective flow areas have been utilized to account for pockets or storage areas, disconnected portions of the cross-section, and/or inactive flow areas that do not actively convey flow downstream.
END DESCRIPTION:
XS GIS Cut Line= 5
     3196816.235    13808939.168     3196760.392    13810480.738
     3196752.138    13810721.374     3196744.857    13810933.638
     3196654.274    13812431.446
#Sta/Elev= 30
       0   30.09  152.72   29.42  377.87    30.4  509.11   29.26  697.42   29.42
  872.52   28.22  903.21   29.13  933.23   28.61 1309.39   29.15 1327.52   28.56
 1362.48   29.35 1432.58   29.06 1612.69   30.27 1626.69    29.7 1642.71   27.85
  1655.9   23.76 1657.16   22.38 1657.75   23.71 1672.72    28.4 1687.73    29.7
 1937.53   29.36 2077.96   30.24 2093.46   29.77 2107.98    29.2 2124.04   29.81
 2223.59   30.08 2479.78   29.92 2539.89   29.24 2624.54   30.46 3496.29   33.37
#Mann= 3 ,-1 , 0
       0     .06       0 1612.69     .04       0 2093.46     .06       0
#XS Ineff= 4 ,-1
    -.87 1594.55   30.56 1628.84 1634.25   29.47 1676.71 1690.05   29.45
 2080.59 2616.27    29.6
Permanent Ineff=
       F       F       F       F
Bank Sta=1626.69,1687.73
XS Rating Curve= 0
Exp/Cntr=.5,.3

Type RM Length L Ch R = 1 ,3875.9  ,681.91,695.79,709.77
BEGIN DESCRIPTION:
XS1 (Interpolated Flow Line)
Due to the length of cross-section and detail of the ground data, ineffective flow areas have been utilized to account for pockets or storage areas, disconnected portions of the cross-section, and/or inactive flow areas that do not actively convey flow downstream.
END DESCRIPTION:
XS GIS Cut Line= 5
     3196720.071    13808934.106     3196660.709    13810476.294
      3196651.82    13810716.294     3196638.462    13811076.975
     3196605.905    13812403.832
#Sta/Elev= 30
       0   30.01   67.73   30.35  142.79   28.63  343.37   29.84  458.02   28.07
  623.14    29.2  993.27   27.98 1596.97   30.01 1613.84   29.98 1628.85   27.11
 1643.86   22.14 1663.49   23.47 1673.88   27.91 1688.92   30.11 1801.26      29
 2064.18   29.69 2083.01   28.27  2094.2   27.08 2124.22   29.93 2169.24   31.32
 2259.27   28.96 2469.33   29.91 2544.36   28.36 2559.36   30.27 2589.37   29.07
 2629.46   31.08 2859.69   32.04 3051.79   31.05 3114.53   32.88 3471.68   33.29
#Mann= 3 ,-1 , 0
       0     .06       0 1596.97     .04       0 2083.01     .06       0
#XS Ineff= 4 ,-1
   -3.21   66.24   30.34   75.04  1571.3   30.25 1705.53 2139.56    30.3
  2170.2 2838.94   31.43
Permanent Ineff=
       F       F       F       F
Bank Sta=1613.84,1688.92
XS Rating Curve= 0
Exp/Cntr=.3,.1

Type RM Length L Ch R = 1 ,3180.1  ,38.65,38.7,39.5
BEGIN DESCRIPTION:
B114-00-00-sv3 (Survey 1698.98 to 1844.34) XS4
Due to the length of cross-section and detail of the ground data, ineffective flow areas have been utilized to account for pockets or storage areas, disconnected portions of the cross-section, and/or inactive flow areas that do not actively convey flow downstream.
END DESCRIPTION:
XS GIS Cut Line= 5
     3196628.968    13808913.861     3196062.857    13810294.675
     3196002.169    13810445.137     3195914.269    13810663.068
     3195307.976    13812148.014
#Sta/Elev= 30
       0   29.16  240.93   28.25  273.36   29.42  429.44   29.75  500.32   28.14
  767.09   27.34  992.83   29.02 1050.32   27.86 1340.01    29.1 1493.99   28.09
 1567.91   29.08 1731.33   28.78 1735.76   28.84 1739.98   28.15 1757.99   21.12
 1760.36   21.86 1761.24   20.83 1765.82   20.47 1785.93   28.03    1792   28.48
 1809.94   29.33 1856.05   28.22 2200.91   28.41 2686.24    29.3 2752.31   27.44
 2784.72   30.16 2833.32   28.79 3271.19   30.29 3367.99   29.11 3493.54   31.01
#Mann= 3 ,-1 , 0
       0     .06       0 1731.33     .04       0 2200.91     .06       0
#XS Ineff= 5 ,-1
     .18  424.12    29.8  426.57 1717.33    29.8 1810.53 2772.81    29.8
 2783.41 3254.46   30.16 3271.28 3418.49   30.29
Permanent Ineff=
       F       F       F       F       F
Bank Sta=1735.76,1792
XS Rating Curve= 0
Exp/Cntr=.5,.3

Type RM Length L Ch R = 1 ,3141.4  ,93.98,92.83,92.4
BEGIN DESCRIPTION:
B114-00-00-s3 (Interpolated Flow Line) XS3
Due to the length of cross-section and detail of the ground data, ineffective flow areas have been utilized to account for pockets or storage areas, disconnected portions of the cross-section, and/or inactive flow areas that do not actively convey flow downstream.
END DESCRIPTION:
XS GIS Cut Line= 4
       3196598.6    13808923.984     3195973.089    13810422.325
     3195870.867     13810666.77     3195267.485    13812112.585
#Sta/Elev= 30
       0   28.28  100.57   28.32  133.07   29.31  149.33   28.35   230.6   28.29
  271.31   29.88  341.82   28.75   409.4   29.53  539.44   27.75  767.01   27.25
  952.52   29.08 1178.19   27.56 1304.21    29.4 1434.34   28.31 1661.96   29.41
 1705.55    28.8    1727   28.01 1743.26   23.74 1751.32    24.1 1753.01      21
 1760.83   20.38 1763.06   20.94 1770.91   26.77 1775.77   27.85 2226.38   28.59
 2538.79   29.02 2720.49   27.44 2771.07   29.08 3376.08   28.75 3455.29   29.82
#Mann= 3 ,-1 , 0
       0     .06       0 1705.55     .04       0 2226.38     .06       0
#XS Ineff= 9 ,-1
    -.58  270.51   29.88  304.07  408.63   29.53  421.25 1662.51   29.41
 1713.03 1722.85    28.7 1774.41 2180.26   28.22 2233.17 2521.71   28.72
 2538.78 2769.27   29.02 2771.68 2925.76   29.08 2961.15 3427.54   29.54
Permanent Ineff=
       F       F       F       F       F       F       F       F       F
Bank Sta=1727,1775.77
XS Rating Curve= 0
Exp/Cntr=.5,.3

Type RM Length L Ch R = 3 ,3095    ,,,
BEGIN DESCRIPTION:
Structure s3 - Red Bluff
END DESCRIPTION:
Bridge Culvert--1,0,-1,-1, 0
Deck Dist Width WeirC Skew NumUp NumDn MinLoCord MaxHiCord MaxSubmerge Is_Ogee
18.4173,56,2.6,0, 91, 58, 28.4424, , .95, 0, 0,0,,
       0   14.66   30.32   57.57    67.5   77.43  112.29   124.4  134.38  134.41
  166.71  213.82  253.88  279.53  328.99  368.12  382.57  384.98  407.18  435.09
  490.57  542.75  544.64  590.83  637.55  750.03  752.79  759.07  818.19  839.97
  853.03  894.44  900.59   905.3  912.93  965.65 1033.16 1064.25 1115.11 1166.32
 1227.07 1253.65 1333.79 1378.33 1443.96 1453.44 1467.24 1522.02  1567.5  1649.2
 1660.03 1723.06 1744.66 1768.29 1835.14 1889.57  1922.1 2005.79 2151.65 2278.59
 2359.62  2368.7  2396.5 2480.01 2495.87 2504.85 2543.81 2555.76 2557.33 2650.04
 2709.92 2712.71 2728.52 2765.48 2807.16 2891.58 2897.21  2899.1 2959.27 3018.52
 3022.59 3047.31 3054.49 3063.12    3173 3180.63 3181.44 3203.67 3208.39  3227.5
 3313.07
    28.2    28.4    28.4    28.4    28.6    28.8    28.8    28.6    28.4    28.4
    28.6    28.6    28.4    28.2      28    27.8    27.6    27.6    27.6    27.4
    27.2      27      27      27    26.8    26.6    26.6    26.6    26.4    26.2
    26.2    26.2    26.2    26.2    26.2    26.4    26.6    26.8      27    27.2
    27.4    27.6    27.8      28    28.2    28.2    28.2    28.4    28.6    28.6
   28.44   28.72    28.7   28.71   28.62   28.62   28.17    28.2      28    27.8
    27.6    27.6    27.6    27.4    27.4    27.4    27.4    27.4    27.4    27.6
    27.8    27.8    27.8      28    28.2    28.4    28.4    28.4    28.6    28.8
    28.8    28.8    28.8    28.6    28.4    28.4    28.4    28.2    28.2    28.2
    28.2
                                                                                
                                                                                
                                                                                
                                                                                
                                                                                
   26.94   27.22    27.2   27.21   27.12   27.12   27.12
                                                                                
                                                                                
                                                                                
        
       0   14.66   30.32   57.57    67.5   77.43  112.29   124.4  134.38  134.41
  166.71  213.82  253.88  279.53  328.99  368.12  382.57  384.98  407.18  435.09
  490.57  542.75  544.64  590.83  637.55  750.03  752.79  759.07  818.19  839.97
  853.03  894.44  900.59   905.3  912.93  965.65 1033.16 1064.25 1115.11 1166.32
 1227.07 1253.65 1333.79 1378.33 1443.96 1453.44 1467.24 1522.02  1567.5  1649.2
 1660.03 1723.06 1744.66 1768.29 1835.14 1889.57  1922.1    1940
    28.2    28.4    28.4    28.4    28.6    28.8    28.8    28.6    28.4    28.4
    28.6    28.6    28.4    28.2      28    27.8    27.6    27.6    27.6    27.4
    27.2      27      27      27    26.8    26.6    26.6    26.6    26.4    26.2
    26.2    26.2    26.2    26.2    26.2    26.4    26.6    26.8      27    27.2
    27.4    27.6    27.8      28    28.2    28.2    28.2    28.4    28.6    28.6
   28.44   28.72    28.7   28.71   28.62   28.62   28.45   28.38
                                                                                
                                                                                
                                                                                
                                                                                
                                                                                
   26.94   27.22    27.2   27.21   27.12   27.12   27.12
Pier Skew, UpSta & Num, DnSta & Num=  ,1752.86, 2 ,1723.57, 2 , 0 , 0 , 0 ,,
     1.5     1.5
      23    27.8
     1.5     1.5
      23    27.8
Pier Skew, UpSta & Num, DnSta & Num=  ,1767.92, 2 ,1749.59, 2 , 0 , 0 , 0 ,,
     1.5     1.5
      23    27.8
     1.5     1.5
      23    27.8
BR Coef=-1 , 1 , 1 ,1.25, 0 ,,,.8,-1,2,0,
WSPro=,,,, 1 ,,,, 0 ,,,, 0 ,,,,-1 ,-1 ,-1 , 0 , 0 , 0 , 0 , 0
BC Design=,, 0 ,, 0 ,,,,,,
BC HTab HWMax=29.88

Type RM Length L Ch R = 1 ,3048.6  ,160.78,151.32,137.48
BEGIN DESCRIPTION:
XS2 (Elev pts adj based on surveyed ds invert and 3180.1)
Left overbank is commercial development/parking lot
Due to the length of cross-section and detail of the ground data, ineffective flow areas have been utilized to account for pockets or storage areas, disconnected portions of the cross-section, and/or inactive flow areas that do not actively convey flow downstream.
END DESCRIPTION:
XS GIS Cut Line= 4
     3196492.313    13808903.739     3195880.391    13810400.103
     3195780.073    13810648.993     3195171.321    13812117.647
#Sta/Elev= 30
       0   28.05  105.93   27.87  203.16   28.83  252.06   28.27  367.08   29.33
  401.59   27.98  666.14   27.99  827.17   26.73 1197.44    28.1 1628.01   28.08
 1678.93   28.87  1692.7   28.73  1711.8   27.27 1716.61   26.19 1718.11   20.47
 1718.81   19.71 1735.07   19.09 1741.22   24.88  1757.9   27.29 1789.73    28.8
  1870.6   28.23 2313.35   29.04 2383.76   28.33 3057.12   28.53 3187.02    29.3
 3203.26   29.16 3219.49   27.91 3251.96   28.85 3446.82   29.96 3474.81   29.59
#Mann= 3 ,-1 , 0
       0    .015       0 1678.93     .04       0 2383.76     .06       0
#XS Ineff= 7 ,-1
    -.42  365.49   29.33  382.69 1674.42   28.89 1691.17 1710.94   28.73
 1758.87 1787.03   28.73 2312.37 3134.38   29.04 3140.21  3170.2   29.06
 3187.69 3407.55    29.3
Permanent Ineff=
       F       F       F       F       F       F       F
Bank Sta=1711.8,1757.9
XS Rating Curve= 0
Exp/Cntr=.5,.3