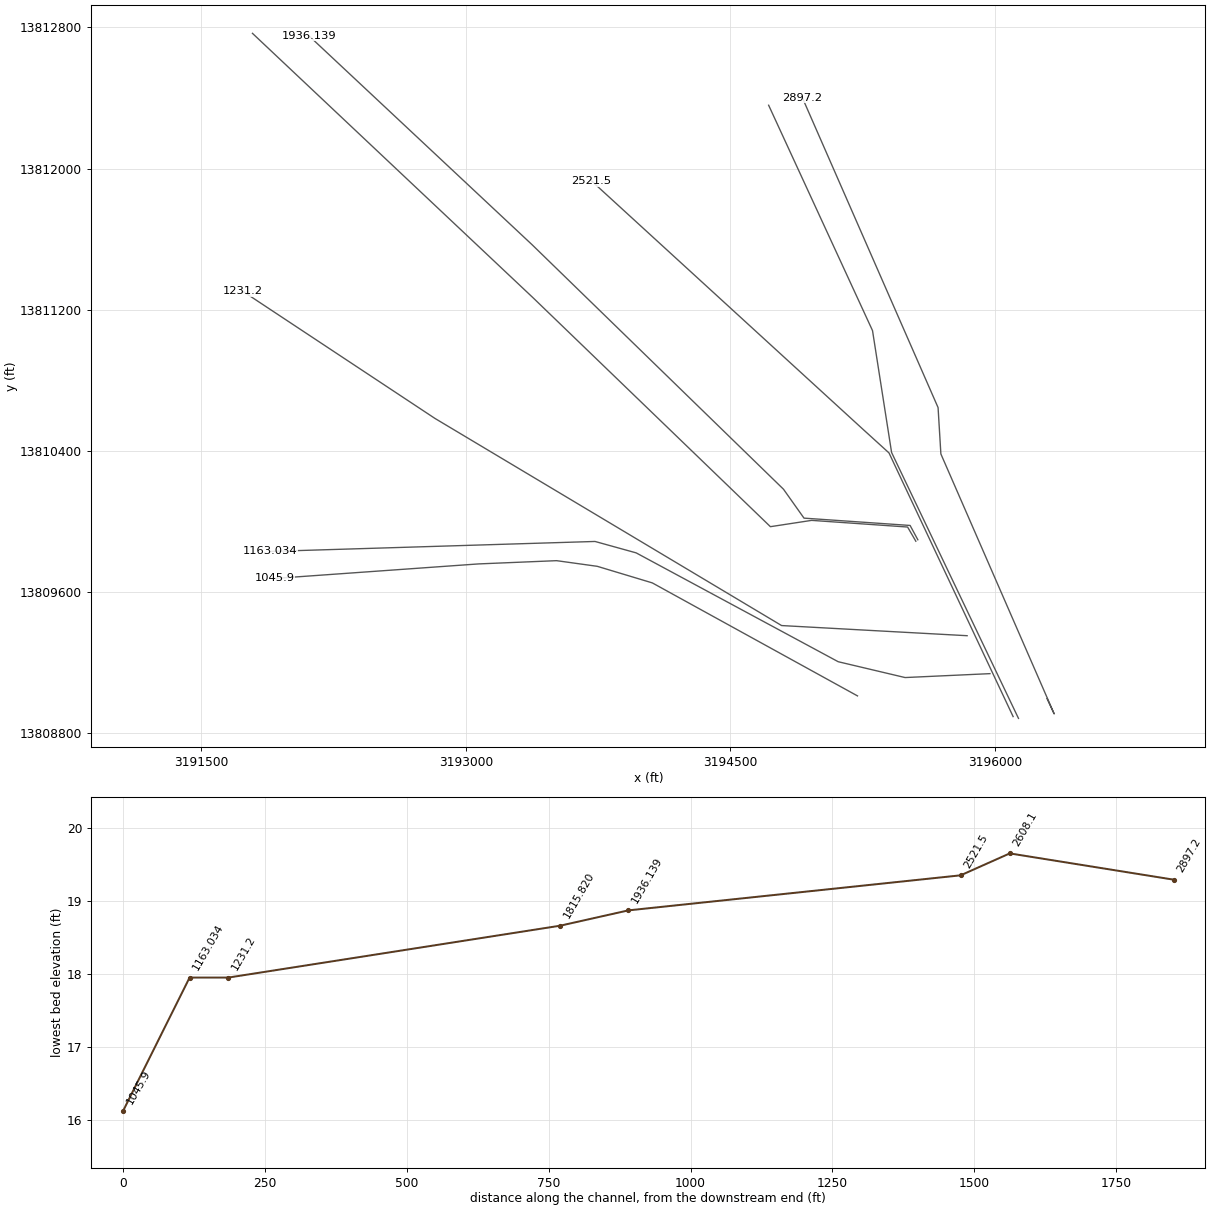
HEC-RAS study B114-00-00.prj: B114-00-00

--- B114-00-00.g08 (geometry) --- (continued)

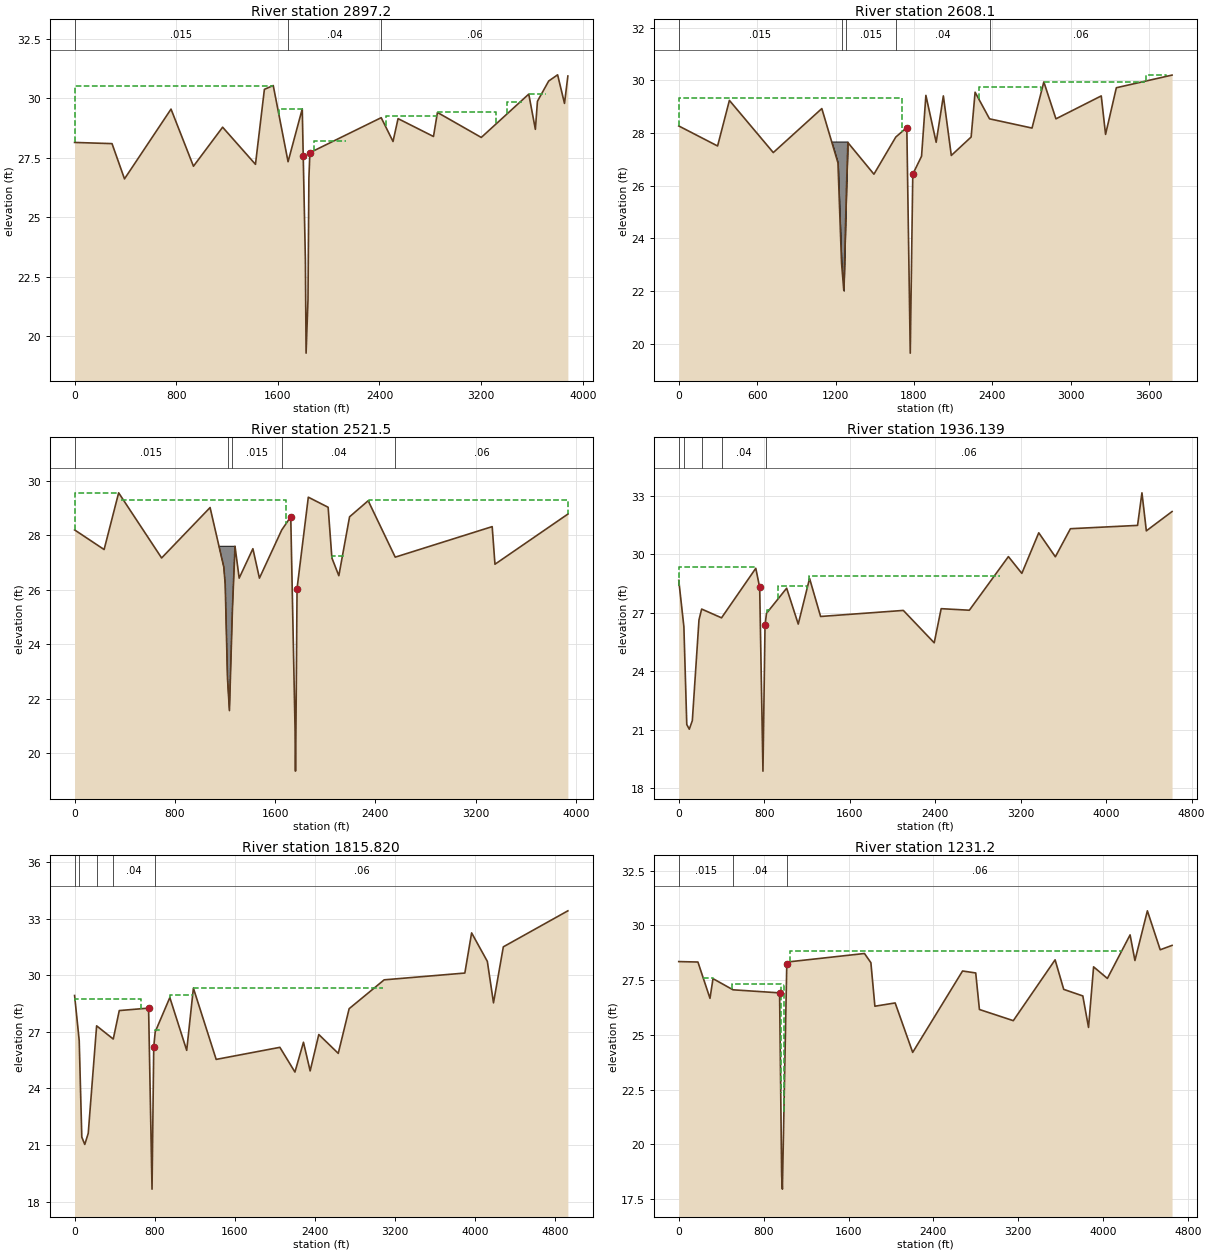
Type RM Length L Ch R = 1 ,2897.2  ,283.71,289.17,291.92
BEGIN DESCRIPTION:
XS1 (Interpolated Flow Line)
Left overbank is commercial development/parking lot
Due to the length of cross-section and detail of the ground data, ineffective flow areas have been utilized to account for pockets or storage areas, disconnected portions of the cross-section, and/or inactive flow areas that do not actively convey flow downstream.
END DESCRIPTION:
XS GIS Cut Line= 5
     3196294.924    13808994.842     3196335.414      13808908.8
     3195693.089    13810382.325     3195677.216    13810645.183
     3194908.135    13812401.078
#Sta/Elev= 30
       0   28.14  294.71   28.09  392.89   26.61  759.21   29.54  935.73   27.14
  1165.3   28.78 1423.77   27.22  1494.1   30.37  1563.7   30.53 1680.43   27.33
 1792.15   29.55 1799.67   27.57 1816.76    23.2 1822.21   19.29 1837.24   21.53
 1844.35   26.64 1852.26   27.71 2413.54   29.18 2506.54   28.18 2546.23   29.14
 2825.08   28.39 2856.13    29.4 3201.26   28.35 3574.96   30.17 3627.03   28.69
  3643.4   29.87 3731.86   30.72 3802.11   30.98 3856.29   29.78 3882.81   30.93
#Mann= 3 ,-1 , 0
       0    .015       0 1680.43     .04       0 2413.54     .06       0
#XS Ineff= 7 ,-1
   -2.45 1560.12   30.53 1608.57 1789.41   29.56 1882.21  2139.2   28.18
 2447.56 2853.66   29.26 2857.32 3314.63   29.41 3400.95 3518.53   29.84
 3574.33 3709.85   30.18
Permanent Ineff=
       F       F       F       F       F       F       F
Bank Sta=1799.67,1852.26
XS Rating Curve= 0
Exp/Cntr=.3,.1

Type RM Length L Ch R = 1 ,2608.1  ,49.51,86.52,111.78
BEGIN DESCRIPTION:
B114-00-00-v5 (Survey 1720.81 to 1808.89)
Left overbank is commercial development/parking lot. detention area blocked out.
Due to the length of cross-section and detail of the ground data, ineffective flow areas have been utilized to account for pockets or storage areas, disconnected portions of the cross-section, and/or inactive flow areas that do not actively convey flow downstream.
END DESCRIPTION:
XS GIS Cut Line= 5
     3196132.963    13808883.494     3195413.723    13810390.579
     3195379.437    13810609.627     3195305.572    13811081.545
     3194716.779    13812358.972
#Sta/Elev= 30
       0   28.27  297.28   27.51  387.63   29.24  723.53   27.26 1095.07   28.93
 1218.58   26.87 1246.04   23.07 1263.59   22.02  1283.8   25.92 1294.52   27.64
 1493.97   26.44 1661.39   27.85 1745.64   28.21 1771.99   19.65 1791.34   26.44
 1858.39   27.12 1891.59   29.43 1970.35   27.65  2025.4   29.41 2086.13   27.15
 2237.95   27.85 2268.32   29.55 2378.81   28.54 2704.07   28.19 2794.51   29.94
 2887.08   28.54 3233.93   29.41 3266.97   27.95 3349.55   29.72 3775.88    30.2
#Mann= 5 ,-1 , 0
       0    .015       0 1246.04     .04       0  1283.8    .015       0
 1661.39     .04       0 2378.81     .06       0
#XS Ineff= 4 ,-1
   -2.53 1707.08   29.32 2298.48 2776.11   29.73 2795.85 3571.92   29.94
 3579.49  3728.4   30.21
Permanent Ineff=
       F       F       F       F
#Block Obstruct= 1 ,-1
 1160.98 1292.68   27.68
Bank Sta=1745.64,1791.34
XS Rating Curve= 0
Exp/Cntr=.3,.1

Type RM Length L Ch R = 1 ,2521.5  ,597.29,585.41,577.68
BEGIN DESCRIPTION:
B114-00-00-v6 (Survey 1702.09 to 1790)
detention area blocked out.
Due to the length of cross-section and detail of the ground data, ineffective flow areas have been utilized to account for pockets or storage areas, disconnected portions of the cross-section, and/or inactive flow areas that do not actively convey flow downstream.
END DESCRIPTION:
XS GIS Cut Line= 4
     3196102.595    13808893.616      3195399.12     13810388.04
      3195239.12    13810533.437     3193713.351    13811929.458
#Sta/Elev= 30
       0    28.2  235.61   27.48  351.66   29.56  694.48   27.17 1081.13   29.02
 1190.47   26.84 1201.74   26.22 1220.15   22.75 1235.56   21.57 1259.51   25.28
 1280.07    27.6 1313.23   26.43 1422.74   27.51 1475.01   26.43 1653.11    28.2
 1724.89   28.68 1759.13   20.91  1761.6   19.35 1763.76   19.36 1775.13   26.05
 1864.96    29.4 2023.18   29.03 2053.12   27.17 2108.47   26.52 2194.09   28.68
 2342.73   29.27 2558.38    27.2 3332.05   28.32 3354.27   26.94 3935.97   28.78
#Mann= 5 ,-1 , 0
       0    .015       0 1220.15     .04       0 1259.51    .015       0
 1653.11     .04       0 2558.38     .06       0
#XS Ineff= 4 ,-1
       0  350.98   29.56   369.9 1686.08   29.28 2054.05  2155.8   27.23
 2346.58 3936.41   29.31
Permanent Ineff=
       F       F       F       F
#Block Obstruct= 1 ,-1
 1146.34 1280.49    27.6
Bank Sta=1724.89,1775.13
XS Rating Curve= 0
Exp/Cntr=.3,.1

Type RM Length L Ch R = 1 ,1936.139,56.47,120.32,166.69
BEGIN DESCRIPTION:
B114-00-00-v7 (Survey 737.94 to 817.43)
Left overbank is apartment complex/parking lot
detention area blocked out.
Due to the length of cross-section and detail of the ground data, ineffective flow areas have been utilized to account for pockets or storage areas, disconnected portions of the cross-section, and/or inactive flow areas that do not actively convey flow downstream.
END DESCRIPTION:
XS GIS Cut Line= 6
     3195562.453    13809895.947      3195518.64    13809977.016
     3194917.214    13810018.515     3194801.024    13810182.325
     3193376.201    13811568.074      3192110.99    13812752.627
#Sta/Elev= 30
       0   28.65   47.87   26.28   75.01   21.26   98.56   21.02  126.96   21.46
  189.33   26.63  214.35   27.18  400.35   26.73  720.86   29.27  757.31   28.29
  787.95   18.87  807.35   26.34  820.97   26.96 1009.82   28.25 1118.17   26.41
 1224.22   28.75 1327.42    26.8 2101.62   27.11  2390.7   25.45 2455.85    27.2
 2719.54   27.12 3085.07   29.87 3210.74   29.01 3369.11   31.09 3524.44   29.86
 3665.54    31.3 4293.78   31.47 4334.88   33.14 4375.97   31.19  4616.6   32.18
#Mann= 5 ,-1 , 0
       0    .015       0   47.87     .04       0  214.35    .015       0
  400.35     .04       0  820.97     .06       0
#XS Ineff= 4 ,-1
    5.69  716.72   29.35  827.05  873.47   27.11  928.32 1200.23   28.34
 1217.29 3003.41   28.86
Permanent Ineff=
       F       F       F       F
#Block Obstruct= 2 , 0
          221.84    27.4
Bank Sta=757.31,807.35
XS Rating Curve= 0
Exp/Cntr=.3,.1

Type RM Length L Ch R = 1 ,1815.820,596.92,584.58,572.84
BEGIN DESCRIPTION:
B114-00-00-v8 (Survey 702.37 to 803.16)
Detention area blocked out.
Due to the length of cross-section and detail of the ground data, ineffective flow areas have been utilized to account for pockets or storage areas, disconnected portions of the cross-section, and/or inactive flow areas that do not actively convey flow downstream.
END DESCRIPTION:
XS GIS Cut Line= 6
     3195551.119    13809887.636     3195504.407    13809968.107
     3194960.389    13810005.817     3194726.804     13809970.08
     3193381.858    13811267.198     3191790.855    13812766.546
#Sta/Elev= 30
       0   28.93   46.29   26.54   72.15   21.42  101.92   21.03  136.49   21.62
  220.32   27.32  386.52   26.62  446.66   28.13  739.62   28.26  774.01   18.66
  791.21    26.2  805.85      27  951.87   28.82 1120.55   26.02 1187.41   29.32
 1415.14   25.54 2051.73   26.18 2202.24   24.87 2287.47   26.45 2354.24   24.93
 2440.67   26.86 2635.14   25.86 2744.06   28.23 3094.13   29.76 3900.26   30.12
 3967.96   32.25 4125.01   30.74 4186.76   28.54 4284.86   31.51 4929.94   33.42
#Mann= 5 ,-1 , 0
       0    .015       0   46.29     .04       0  220.32    .015       0
  386.52     .04       0  805.85     .06       0
#XS Ineff= 4 ,-1
    5.69  665.53   28.73  807.74  853.24   27.11  949.94 1183.16   28.93
 1188.22 3083.05   29.32
Permanent Ineff=
       F       F       F       F
#Block Obstruct= 2 , 0
          216.15   27.33
Bank Sta=739.62,791.21
XS Rating Curve= 0
Exp/Cntr=.3,.1

Type RM Length L Ch R = 1 ,1231.2  ,86.96,68.2,32.85
BEGIN DESCRIPTION:
B114-00-00-sv4 (Survey 894.49 to 1049.43) XS4
Due to the length of cross-section and detail of the ground data, ineffective flow areas have been utilized to account for pockets or storage areas, disconnected portions of the cross-section, and/or inactive flow areas that do not actively convey flow downstream.
END DESCRIPTION:
XS GIS Cut Line= 6
      3195841.85    13809352.091     3195304.874    13809381.383
     3194998.484    13809398.197      3194790.23    13809409.626
      3192825.11     13810583.86      3191735.18    13811305.062
#Sta/Elev= 30
       0   28.35  180.62   28.33  294.31   26.67   322.8   27.57  511.43   27.06
  950.35   26.92  969.82   18.59  976.73   17.95 1018.21   28.25 1022.86   28.33
  1750.5   28.72 1810.81    28.3 1848.57   26.31 2039.53   26.46 2204.82    24.2
 2674.83   27.92 2798.93   27.83 2833.88   26.16 3153.16   25.65 3547.05   28.43
 3628.35   27.08 3808.22   26.78 3862.18   25.34 3909.88   28.11 4039.77   27.58
  4253.8   29.57 4299.55    28.4 4416.89   30.67 4537.68   28.89 4649.35   29.09
#Mann= 3 ,-1 , 0
       0    .015       0  511.43     .04       0 1022.86     .06       0
#XS Ineff= 4 ,-1
  226.63  321.74   27.61   498.2  961.07   27.31  990.93 1017.27   27.29
 1050.46  4178.1   28.83
Permanent Ineff=
       F       F       F       F
Bank Sta=950.35,1018.21
XS Rating Curve= 0
Exp/Cntr=.5,.3

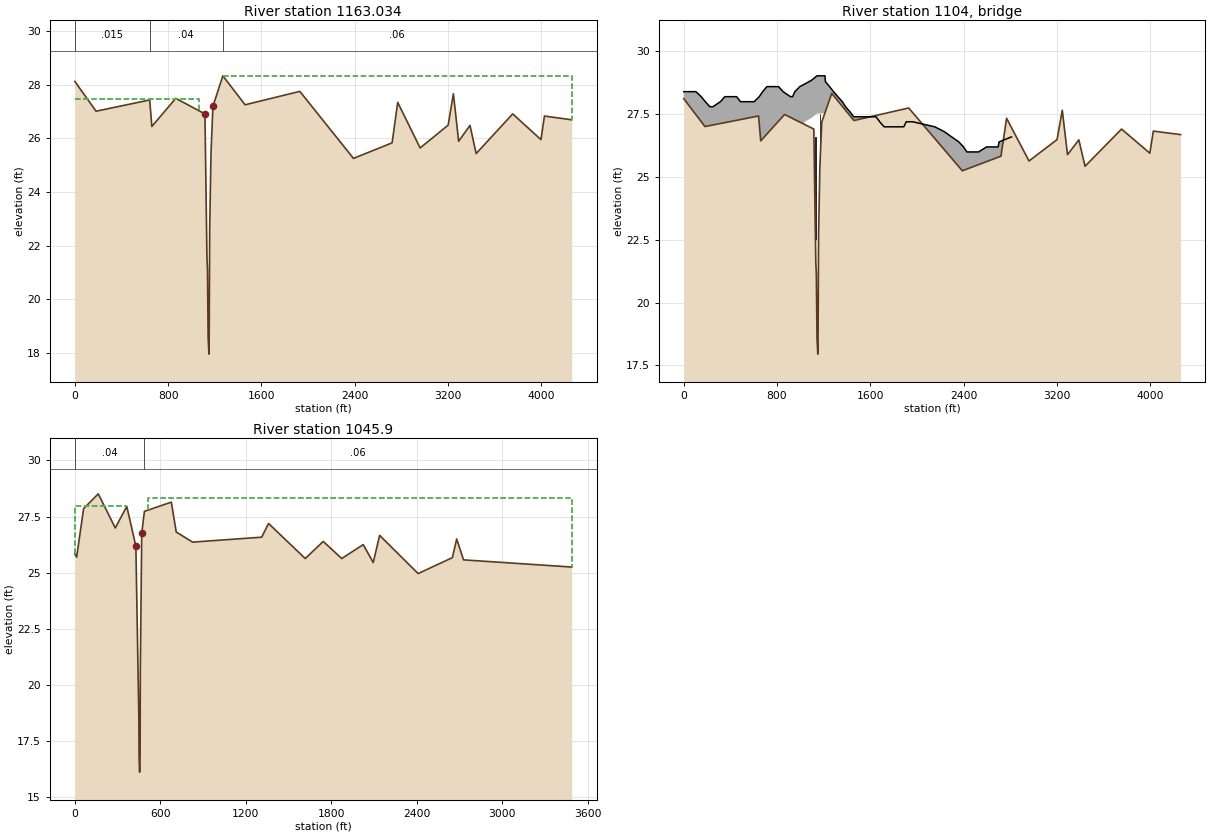
Type RM Length L Ch R = 1 ,1163.034,126.47,117.4,117.2
BEGIN DESCRIPTION:
B114-00-00-s4 XS3
Due to the length of cross-section and detail of the ground data, ineffective flow areas have been utilized to account for pockets or storage areas, disconnected portions of the cross-section, and/or inactive flow areas that do not actively convey flow downstream.
END DESCRIPTION:
XS GIS Cut Line= 6
     3195971.428    13809137.044     3195490.256     13809114.87
     3195110.998    13809204.644     3193965.774    13809821.643
     3193732.566    13809886.315     3191888.287     13809829.66
#Sta/Elev= 30
       0   28.12  181.74   27.01  641.67   27.43  660.09   26.44  864.92   27.49
 1115.54   26.91 1132.62   21.56 1137.14   21.13 1142.82   18.59 1149.73   17.95
 1151.79   18.52 1156.33   22.66 1167.39   25.43 1183.84   27.19 1269.12   28.33
 1459.83   27.25 1929.32   27.75  2389.3   25.25  2720.7   25.83 2768.75   27.34
 2961.05   25.64 3201.36   26.49 3246.42   27.66 3291.47   25.89 3388.51   26.48
 3441.66   25.43 3755.02   26.91 3997.34   25.95 4027.38   26.83 4261.02   26.69
#Mann= 3 ,-1 , 0
       0    .015       0  641.67     .04       0 1269.12     .06       0
#XS Ineff= 2 , 0
         1063.83   27.47 1268.41           28.33
Permanent Ineff=
       F       F
Bank Sta=1115.54,1183.84
XS Rating Curve= 0
Exp/Cntr=.5,.3

Type RM Length L Ch R = 3 ,1104    ,,,
BEGIN DESCRIPTION:
Structure s4 - Spencer Hwy
END DESCRIPTION:
Bridge Culvert--1,0,-1,-1, 0
Deck Dist Width WeirC Skew NumUp NumDn MinLoCord MaxHiCord MaxSubmerge Is_Ogee
10.1382,96.9,2.6,0, 55, 48, , , .95, 0, 0,0,,
       0   71.73  104.15  149.49  185.13  223.86  249.81  314.36  352.23  454.03
  486.28  604.16  647.35  676.81   713.3  812.83  852.25  914.73  933.26  953.04
  995.47 1035.81 1094.88 1143.08 1188.29  1211.6 1214.88  1250.7 1284.47 1321.42
    1360 1387.61 1424.81 1457.41 1544.97 1648.56 1680.76 1718.84 1844.03 1854.35
 1887.57 1907.62 1963.86 2153.62 2236.93  2297.2 2359.19  2399.4  2428.4 2528.67
 2596.96 2602.76 2696.13 2704.89 2811.27
    28.4    28.4    28.4    28.2      28    27.8    27.8      28    28.2    28.2
      28      28    28.2    28.4    28.6    28.6    28.4    28.2    28.2    28.4
    28.6    28.7   28.85   29.03   29.03   29.03    28.8    28.6    28.4    28.2
      28    27.8    27.6    27.4    27.4    27.4    27.2      27      27      27
      27    27.2    27.2      27    26.8    26.6    26.4    26.2      26      26
    26.2    26.2    26.2    26.4    26.6
                                                                                
                                                                                
            27.2   27.35   27.53   27.53   27.53
                                                                                
                                                                                
                                        
 -632.75 -600.33 -554.99 -519.35 -480.62 -454.67 -390.12 -352.25 -250.45  -218.2
 -100.32  -57.13  -27.67    8.82  108.35  147.77  210.25  228.78  248.56  290.99
  331.33   390.4   438.6  483.81  507.12   510.4  546.22  579.99  616.94  655.52
  683.13  720.33  752.93  840.49  944.08  976.28 1014.36 1139.55 1149.87 1183.09
 1203.14 1259.38 1449.14 1532.45 1592.72 1654.71 1694.92 1723.92
    28.4    28.4    28.2      28    27.8    27.8      28    28.2    28.2      28
      28    28.2    28.4    28.6    28.6    28.4    28.2    28.2    28.4    28.6
    28.7   28.85   29.03   29.03   29.03    28.8    28.6    28.4    28.2      28
    27.8    27.6    27.4    27.4    27.4    27.2      27      27      27      27
    27.2    27.2      27    26.8    26.6    26.4    26.2      26
                                                                                
                                                                                
    27.2   27.35   27.53   27.53   27.53
                                                                                
                                                                
Pier Skew, UpSta & Num, DnSta & Num=  ,1129.47, 4 ,442.89, 4 , 3 , 3 , 0 ,,
    1.35    1.35     2.5     2.5
      16    24.1    24.1    26.6
    1.35    1.35     2.5     2.5
      16    24.1    24.1    26.6
Pier Skew, UpSta & Num, DnSta & Num=  ,1168.48, 2 ,470, 2 , 0 , 0 , 0 ,,
     2.5     2.5
   24.02      28
     2.5     2.5
   24.02      28
BR Coef=-1 , 1 , 1 ,1.25, 0 ,,,.8,0,2,0,
WSPro=,,,, 1 ,,,, 0 ,,,, 0 ,,,,-1 ,-1 ,-1 , 0 , 0 , 0 , 0 , 0
BC Design=,, 0 ,, 0 ,,,,,,
BC HTab HWMax=28.37

Type RM Length L Ch R = 1 ,1045.9  ,119.79,226.34,260.68
BEGIN DESCRIPTION:
B114-00-00-v9 (Survey 381.85 to 495.94) XS2
Due to the length of cross-section and detail of the ground data, ineffective flow areas have been utilized to account for pockets or storage areas, disconnected portions of the cross-section, and/or inactive flow areas that do not actively convey flow downstream.
END DESCRIPTION:
XS GIS Cut Line= 6
     3195220.465    13809010.874     3194057.477    13809651.376
     3193745.375    13809745.409     3193514.801    13809777.433
     3193071.439    13809758.959     3191916.125    13809676.552
#Sta/Elev= 30
       0   25.83   12.29   25.69   61.39   27.85  164.04   28.51  283.81   26.99
  364.41   27.95  428.25   26.18  449.12   18.56  450.72   16.76  454.68   16.12
  457.94   16.84  459.52   20.63  469.39   26.76  488.38   27.73  677.34   28.14
  711.62   26.81  826.66   26.36 1311.51   26.58  1359.9   27.19 1617.44   25.63
 1743.76   26.39 1873.95   25.63 2024.62   26.25 2094.79   25.45 2139.92   26.66
 2410.19   24.96  2650.8   25.67 2680.88    26.5  2729.1   25.57 3488.44   25.25
#Mann= 2 ,-1 , 0
       0     .04       0  488.38     .06       0
#XS Ineff= 2 , 0
       0  364.32   27.95  512.93       0   28.32
Permanent Ineff=
       F       F
Bank Sta=428.25,469.39
XS Rating Curve= 0
Exp/Cntr=.5,.3