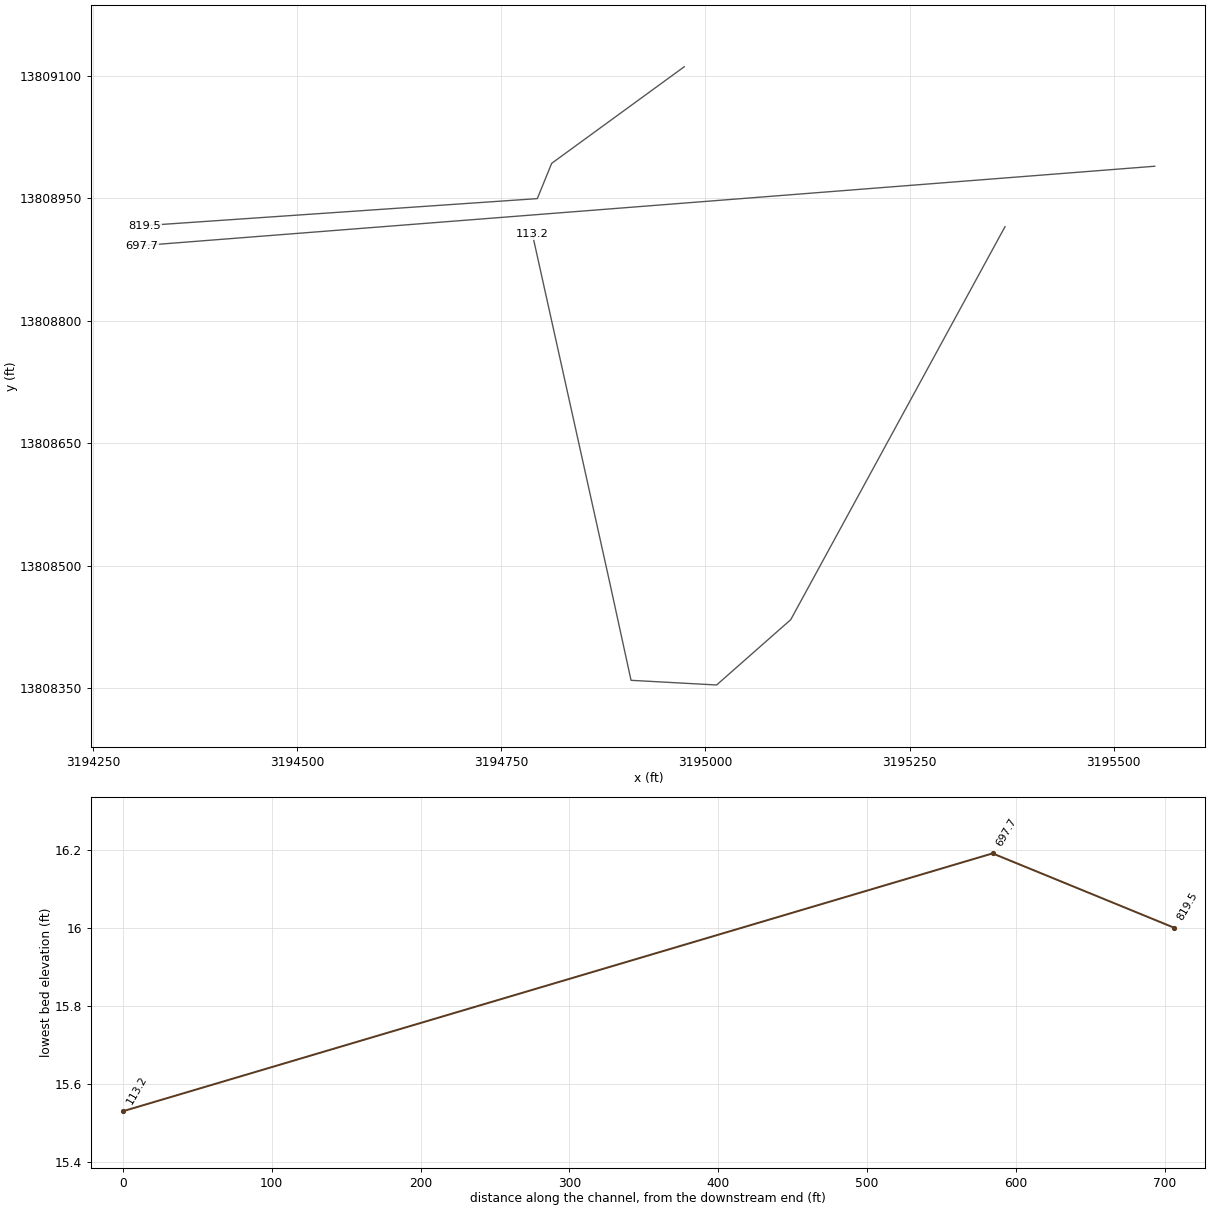
HEC-RAS study B114-00-00.prj: B114-00-00

--- B114-00-00.g08 (geometry) --- (continued)

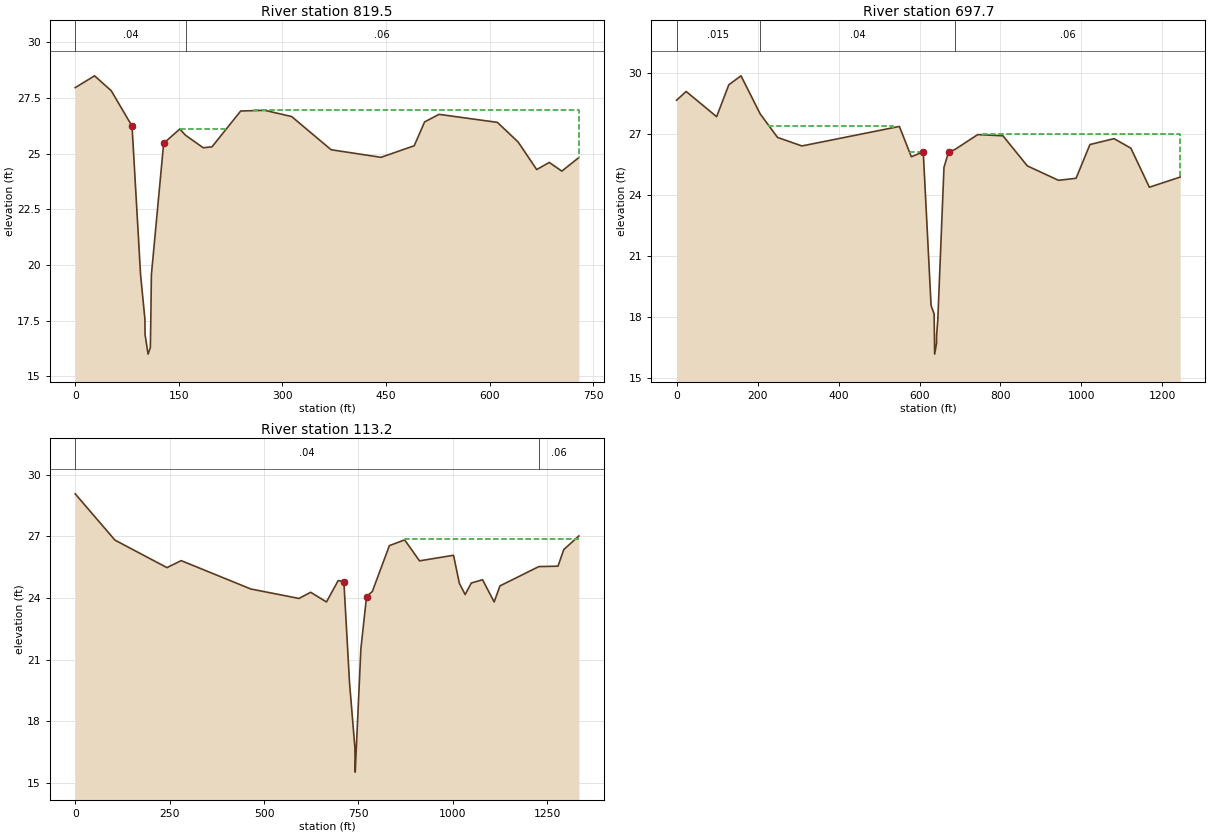
Type RM Length L Ch R = 1 ,819.5   ,146.96,121.86,83.4
BEGIN DESCRIPTION:
B114-00-00-v10 (Survey 52.16 to 151.31) XS1
Due to the length of cross-section and detail of the ground data, ineffective flow areas have been utilized to account for pockets or storage areas, disconnected portions of the cross-section, and/or inactive flow areas that do not actively convey flow downstream.
END DESCRIPTION:
XS GIS Cut Line= 4
     3194974.146    13809110.834     3194811.761    13808992.539
     3194794.189    13808949.334     3194313.878    13808916.313
#Sta/Elev= 30
       0   27.97   27.99    28.5   52.16   27.83   82.25   26.24   94.58   19.57
   100.9   17.56  101.08   16.88  105.44      16  108.74   16.29  109.46   17.64
  110.23   19.56     128   25.47  151.31   26.11  159.72   25.83   185.2   25.27
  197.95   25.31   239.5   26.92  274.45   26.95  313.28   26.67  370.38   25.18
  442.63   24.84  490.66   25.36   505.7   26.43  526.54   26.77  610.95   26.41
  641.02   25.53  667.94   24.29  686.12   24.61  704.28   24.22  728.99   24.83
#Mann= 2 ,-1 , 0
       0     .04       0  159.72     .06       0
#XS Ineff= 2 ,-1
  151.39   216.3   26.11  258.68  729.09   26.98
Permanent Ineff=
       F       F
Bank Sta=82.25,128
XS Rating Curve= 0
Exp/Cntr=.3,.1

Type RM Length L Ch R = 1 ,697.7   ,589.87,584.42,474.46
BEGIN DESCRIPTION:
B114-00-00-v11 (Survey 579.77 to 671.93)
Right overbank is commercial development/parking lot
Due to the length of cross-section and detail of the ground data, ineffective flow areas have been utilized to account for pockets or storage areas, disconnected portions of the cross-section, and/or inactive flow areas that do not actively convey flow downstream.
END DESCRIPTION:
XS GIS Cut Line= 4
     3195550.291    13808988.987     3195051.818    13808949.942
     3194808.643    13808930.895      3194310.17     13808891.85
#Sta/Elev= 30
       0   28.68   23.72   29.11   98.95   27.87  129.04   29.44  159.13   29.88
  206.44   28.01  249.41   26.85  309.59   26.43  550.33   27.39  579.77    25.9
  609.25   26.14   628.6   18.58  636.07   18.17  637.43   16.19  642.06   16.72
  642.24   17.12  645.12   17.86  660.47   25.38  671.93   26.14  687.74   26.26
  743.92   26.99  806.11   26.93  866.29   25.45   943.3   24.74  986.66   24.84
 1020.92    26.5 1080.53   26.79 1122.07   26.32 1167.72    24.4 1243.92    24.9
#Mann= 3 ,-1 , 0
       0    .015       0  206.44     .04       0  687.74     .06       0
#XS Ineff= 3 ,-1
  226.83  534.93    27.4  576.32  608.55   26.14  756.92 1244.64   27.04
Permanent Ineff=
       F       F       F
Bank Sta=609.25,671.93
XS Rating Curve= 0
Exp/Cntr=.3,.1

Type RM Length L Ch R = 1 ,113.2   ,0,0,0
BEGIN DESCRIPTION:
741.36 Interpolated Flow Line
Due to the length of cross-section and detail of the ground data, ineffective flow areas have been utilized to account for pockets or storage areas, disconnected portions of the cross-section, and/or inactive flow areas that do not actively convey flow downstream.
END DESCRIPTION:
XS GIS Cut Line= 6
      3195366.92    13808915.028     3195104.516    13808433.751
     3195013.723    13808353.751      3194908.96    13808359.465
     3194882.929    13808478.831     3194788.185    13808905.806
#Sta/Elev= 30
       0   29.07  105.03   26.82  242.88   25.48  280.45   25.82  464.98   24.44
  592.46   23.98  623.43   24.28  665.28   23.81  696.29   24.85  711.31    24.8
  726.34   19.88  740.51   16.72  741.36   15.53  756.38   21.53   771.4   24.07
   786.7   24.32  831.89   26.55  872.27   26.83  911.63   25.81 1001.72   26.08
 1017.09   24.72 1032.45   24.17 1048.71   24.73 1078.55   24.89 1109.28   23.81
 1124.64   24.59 1227.57   25.53 1278.29   25.55 1293.66   26.36 1333.62   27.02
#Mann= 2 ,-1 , 0
       0     .04       0 1227.57     .06       0
#XS Ineff= 2 , 0
                          872.81           26.85
Permanent Ineff=
       F       F
Bank Sta=711.31,771.4
XS Rating Curve= 0
Exp/Cntr=.3,.1

Chan Stop Cuts=-1